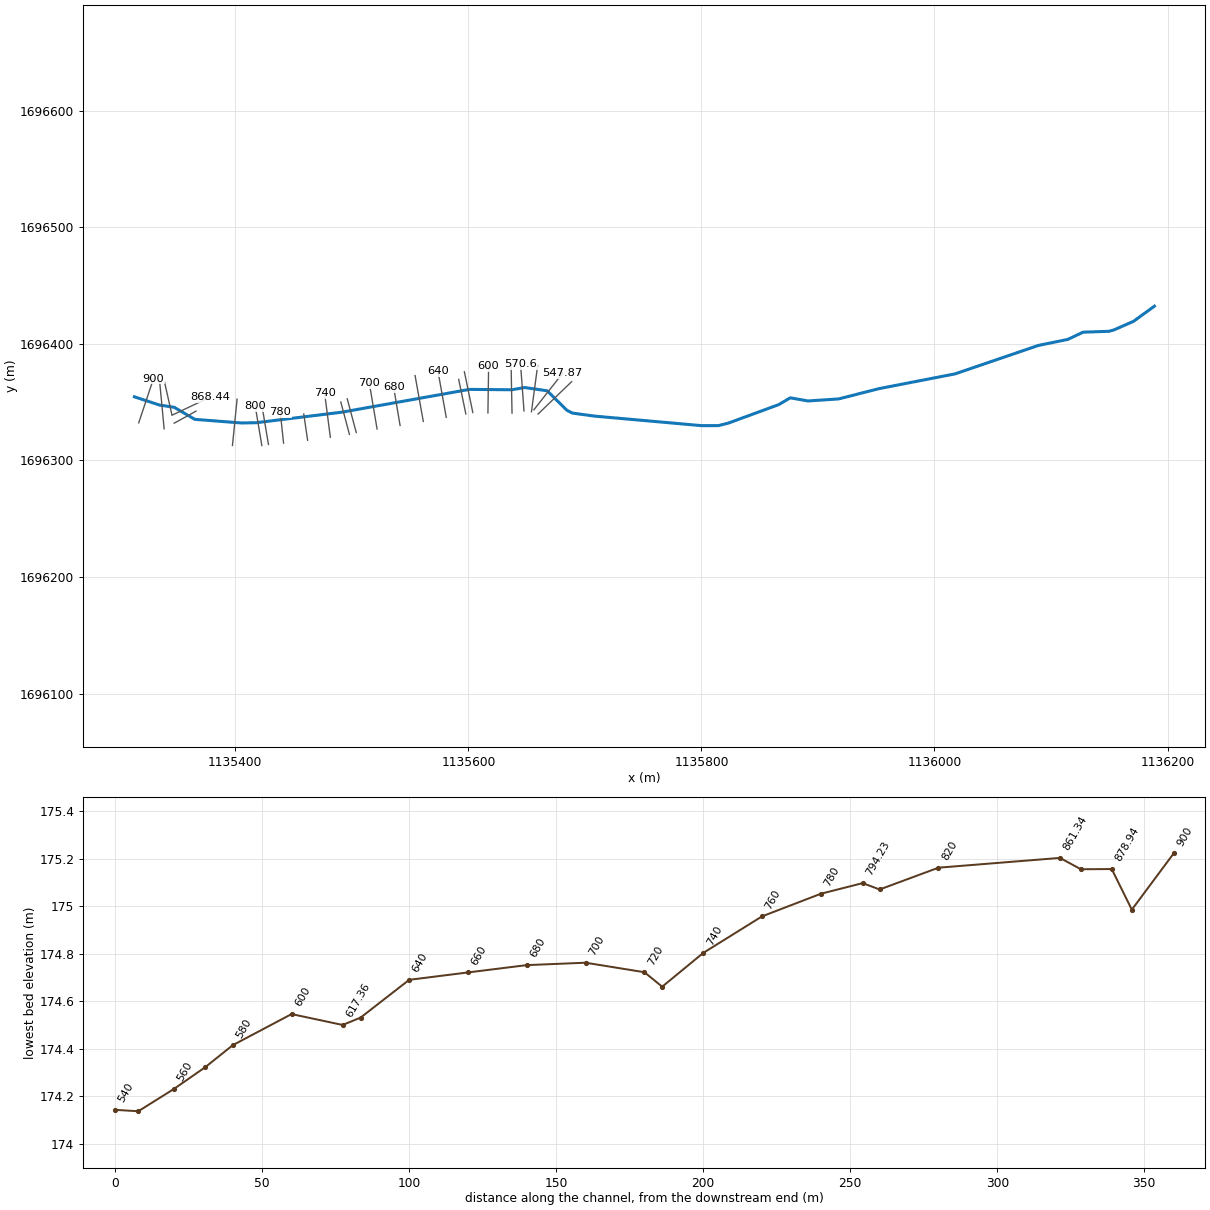
--- AcequiaDiseño.prj (project) ---

Proj Title=Acequia Diseño
Current Plan=p02
Default Exp/Contr=0.3,0.1
SI Units
Geom File=g01
Flow File=f01
Flow File=f02
Plan File=p01
Plan File=p02
Y Axis Title=Elevation
X Axis Title(PF)=Main Channel Distance
X Axis Title(XS)=Station
BEGIN DESCRIPTION:
END DESCRIPTION:
DSS Export Rating Curves= 0
DSS Export Rating Curve Sorted= 0
DSS Export Volume Flow Curves= 0
DXF OffsetX= 0
DXF OffsetY= 0
DXF ScaleX= 1
DXF ScaleY= 10

--- AcequiaDiseño.p02 (plan) ---

Plan Title=Plan 02
Program Version=5.06
Short Identifier=Plan 02
Geom File=g01
Flow File=f02
Subcritical Flow
K Sum by GR= 0
Std Step Tol= 0.01
Critical Tol= 0.01
Num of Std Step Trials= 20
Max Error Tol= 0.3
Flow Tol Ratio= 0.001
Split Flow NTrial= 30
Split Flow Tol= 0.02
Split Flow Ratio= 0.02
Log Output Level= 0
Friction Slope Method= 1
Unsteady Friction Slope Method= 2
Unsteady Bridges Friction Slope Method= 1
Parabolic Critical Depth
Global Vel Dist= 0 , 0 , 0
Global Log Level= 0
CheckData=True
Encroach Param=-1 ,0,0, 0
Computation Interval=1MIN
Output Interval=1HOUR
Instantaneous Interval=1HOUR
Mapping Interval=1HOUR
Computation Time Step Use Courant=        0
Computation Time Step Use Time Series=    0
Computation Time Step Count To Double=0
Computation Time Step Max Doubling=0
Computation Time Step Max Halving=0
Computation Time Step Residence Courant=0
Run HTab= 0
Run UNet= 0
Run Sediment= 0
Run PostProcess= 0
Run WQNet= 0
Run RASMapper= 0
UNET Theta= 1
UNET Theta Warmup= 1
UNET ZTol= 0.02
UNET ZSATol= 0.02
UNET MxIter= 20
UNET Max Iter WO Improvement= 0
UNET MaxInSteps= 0
UNET DtIC= 0
UNET DtMin= 0
UNET MaxCRTS= 20
UNET WFStab= 2
UNET SFStab= 1
UNET WFX= 1
UNET SFX= 1
UNET 1D Methodology=Finite Difference
UNET DSS MLevel= 4
UNET Pardiso=0
UNET DZMax Abort= 100
UNET Use Existing IB Tables=-1
UNET Froude Reduction=False
UNET Froude Limit= 0.8
UNET Froude Power= 4
UNET D1 Cores= 0
UNET D2 Coriolis=0
UNET D2 Cores= 0
UNET D2 Theta= 1
UNET D2 Theta Warmup= 1
UNET D2 Z Tol= 0.01
UNET D2 Volume Tol= 0.01
UNET D2 Max Iterations= 20
UNET D2 Equation= 0
UNET D2 RampUpFraction=0.1
UNET D2 TimeSlices= 1
UNET D2 BCVolumeCheck=0
UNET D1D2 MaxIter= 0
UNET D1D2 ZTol=0.01
UNET D1D2 QTol=0.1
UNET D1D2 MinQTol=1
Write IC File= 0
Write IC File at Fixed DateTime=0
Write IC File at Sim End=0
Echo Input=False
Echo Parameters=False
Echo Output=False
Write Detailed= 0
HDF Write Warmup=0
HDF Write Time Slices=0
HDF Flush=0
HDF Face Node Velocities=0
HDF Compression= 1
HDF Chunk Size= 1
HDF Spatial Parts= 1
HDF Use Max Rows=0
HDF Fixed Rows= 1
Calibration Method= 0
Calibration Iterations= 20
Calibration Max Change=0.05
Calibration Tolerance=0.2
Calibration Maximum=1.5
Calibration Minimum=0.5
Calibration Optimization Method= 1
WQ AD Non Conservative
WQ ULTIMATE=-1
WQ Max Comp Step=1HOUR
WQ Output Interval=15MIN
WQ Output Selected Increments= 0
WQ Output face flow=0
WQ Output face velocity=0
WQ Output face area=0
WQ Output face dispersion=0
WQ Output cell volume=0
WQ Output cell surface area=0
WQ Output cell continuity=0
WQ Output cumulative cell continuity=0
WQ Output face conc=0
WQ Output face dconc_dx=0
WQ Output face courant=0
WQ Output face peclet=0
WQ Output face adv mass=0
WQ Output face disp mass=0
WQ Output cell mass=0
WQ Output cell source sink temp=0
WQ Output nsm pathways=0
WQ Output nsm derived pathways=0
WQ Output MaxMinRange=-1
WQ Daily Max Min Mean=-1
WQ Daily Range=0
WQ Daily Time=0
WQ Create Restart=0
WQ Fixed Restart=0
WQ System Summary=0
WQ Write To DSS=0
WQ Use Fixed Temperature=0
Sorting and Armoring Iterations= 10
XS Update Threshold= 0.02
Bed Roughness Predictor= 0
Hydraulics Update Threshold= 0.02
Energy Slope Method= 1
Volume Change Method= 1
Sediment Retention Method= 0
XS Weighting Method= 0
Number of US Weighted Cross Sections= 1
Number of DS Weighted Cross Sections= 1
Upstream XS Weight=0
Main XS Weight=1
Downstream XS Weight=0
Number of DS XS's Weighted with US Boundary= 1
Upstream Boundary Weight= 1
Weight of XSs Associated with US Boundary= 0
Number of US XS's Weighted with DS Boundary= 1
Downstream Boundary Weight= 0.5
Weight of XSs Associated with DS Boundary= 0.5
Percentile Method= 0
Sediment Output Level= 3
Mass or Volume Output= 0
Output Increment Type= 1
Profile and TS Output Increment= 1
XS Output Flag= 0
XS Output Increment= 10
Write Gradation File= 0
Read Gradation Hotstart= 0
Write HDF5 File= 1
Write Binary Output= 1
Write DSS Sediment File= 0
SV Curve= 0
Specific Gage Flag= 0

--- AcequiaDiseño.p01 (plan) ---

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Plan Title=Plan 01
Program Version=5.07
Short Identifier=Plan 01
Geom File=g01

--- AcequiaDiseño.f02 (steady flow) ---

Flow Title=Flow 02
Program Version=5.06
Number of Profiles= 3
Profile Names=PF 1,PF 2,PF 3
River Rch & RM=Acequia Penzo,Eje             ,900
     .12     .12     .12
River Rch & RM=Acequia Penzo,Eje             ,820
    .473    .579    .675
River Rch & RM=Acequia Penzo,Eje             ,520
    .682    .835    .972
River Rch & RM=Acequia Penzo,Eje             ,40
    .833   1.019   1.187
Boundary for River Rch & Prof#=Acequia Penzo,Eje             , 1
Up Type= 0
Dn Type= 3
Dn Slope=0.035
Boundary for River Rch & Prof#=Acequia Penzo,Eje             , 2
Up Type= 0
Dn Type= 3
Dn Slope=0.035
Boundary for River Rch & Prof#=Acequia Penzo,Eje             , 3
Up Type= 0
Dn Type= 3
Dn Slope=0.035
DSS Import GetInterval= 0
DSS Import GetPeak= 0
DSS Import FillOption= 0

--- AcequiaDiseño.f01 (steady flow) ---

Flow Title=Flow 01
Program Version=5.07
Number of Profiles= 3
Profile Names=PF 1,PF 2,PF 3
River Rch & RM=Acequia Penzo,Eje             ,900
    .473    .579    .675
River Rch & RM=Acequia Penzo,Eje             ,868.44
    .682    .835    .972
River Rch & RM=Acequia Penzo,Eje             ,392.56
    .833   1.019   1.187
Boundary for River Rch & Prof#=Acequia Penzo,Eje             , 1
Up Type= 0
Dn Type= 3
Dn Slope=0.035
Boundary for River Rch & Prof#=Acequia Penzo,Eje             , 2
Up Type= 0
Dn Type= 3
Dn Slope=0.035
Boundary for River Rch & Prof#=Acequia Penzo,Eje             , 3
Up Type= 0
Dn Type= 3
Dn Slope=0.035
DSS Import GetInterval= 0
DSS Import GetPeak= 0
DSS Import FillOption= 0

--- AcequiaDiseño.g01 (geometry) ---

Geom Title=Geometria 1
Program Version=5.06

River Reach=Acequia Penzo   ,Eje
Reach XY= 30
      1136188.73      1696432.42      1136170.84      1696419.43
      1136153.87      1696411.98      1136149.63      1696410.84
      1136127.52       1696410.1       1136114.4      1696403.89
       1136089.1      1696398.71      1136017.64      1696374.31
      1135952.42      1696361.65      1135917.72      1696352.81
      1135891.41      1696351.08      1135876.24      1696353.75
      1135866.33      1696347.93      1135822.86      1696331.97
      1135814.66      1696329.91      1135799.99      1696329.89
      1135708.16      1696338.08      1135689.26      1696340.66
      1135684.53      1696343.08      1135667.62      1696359.79
      1135648.21       1696362.6      1135637.41      1696360.67
      1135600.92        1696361.      1135491.58      1696341.46
      1135418.22      1696332.43      1135405.35      1696332.17
      1135365.23       1696335.3       1135347.6      1696345.59
      1135334.94      1696347.56       1135313.4      1696354.62

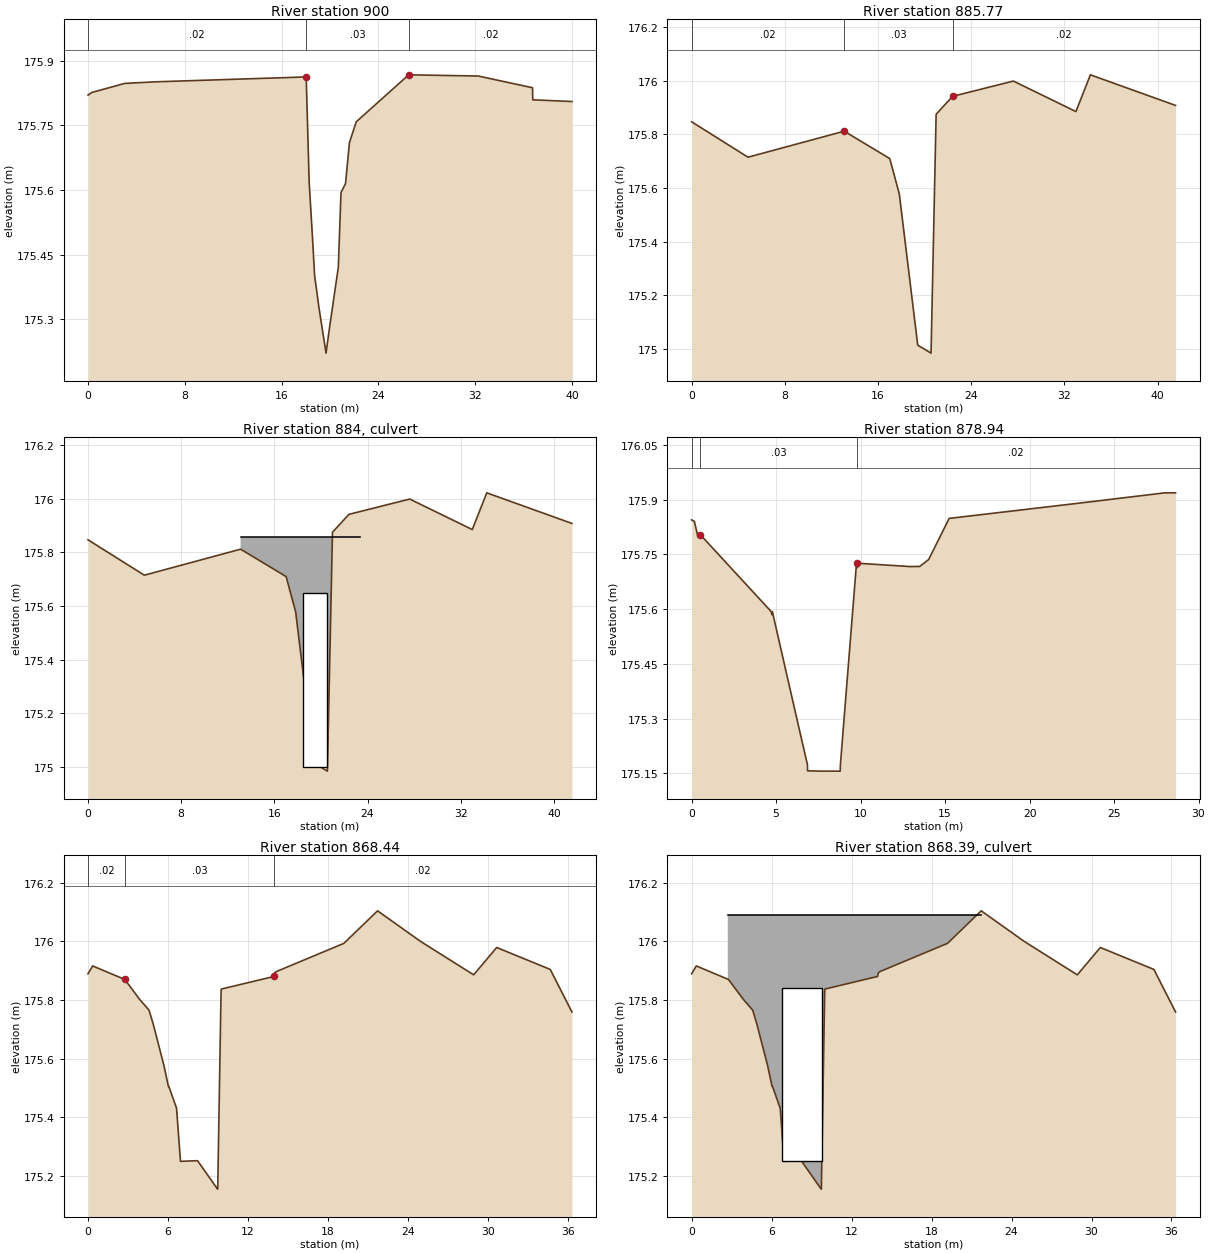
Type RM Length L Ch R = 1 ,900     ,15.6621,14.2299,14.0869
XS GIS Cut Line= 3
      1135317.08       1696332.3      1135323.43      1696351.27
      1135329.77      1696370.24
#Sta/Elev= 23
       0175.8199    .313 175.826  3.0349 175.847  5.6019175.8507 18.0371 175.862
 18.0801 175.819 18.2819175.6178 18.5681 175.484   18.73 175.402 19.0771175.3301
 19.6751175.2219 20.0001 175.288  20.054175.2981  20.691175.4209  20.912175.5941
 21.2881175.6151 21.6109175.7099  22.173 175.758 26.5078175.8669 32.2509175.8641
 36.7421 175.837  36.765 175.809 40.0001 175.805
#Mann= 3 , 0 , 0
       0     .02       0 18.0371     .03       0 26.5078     .02       0
Bank Sta=18.0371,26.5078
XS Rating Curve= 0 ,0
Exp/Cntr=0.3,0.1

Type RM Length L Ch R = 1 ,885.77  ,7.435,6.83,6.6989
XS GIS Cut Line= 3
      1135338.91      1696327.14      1135337.02       1696347.1
      1135334.98       1696368.5
#Sta/Elev= 13
       0 175.847   4.839175.7151 13.1009 175.812   17.01175.7099  17.829175.5779
   19.41175.0149 20.5521174.9851 20.9901175.8751  22.401175.9418  27.621175.9988
 32.9891175.8851 34.2339 176.022 41.5448 175.908
#Mann= 3 , 0 , 0
       0     .02       0 13.1009     .03       0  22.401     .02       0
Bank Sta=13.1009,22.401
XS Rating Curve= 0 ,0
Exp/Cntr=0.3,0.1

Type RM Length L Ch R = 2 ,884     ,,,
BEGIN DESCRIPTION:
Carrera 9
END DESCRIPTION:
Bridge Culvert--1,0,-1,-1, 0
Deck Dist Width WeirC Skew NumUp NumDn MinLoCord MaxHiCord MaxSubmerge Is_Ogee
0.05,5.94,1.4,0, 2, 2, , , 0.98, 0, 0,0,,
    13.1   23.32
 175.857 175.857
     175     175
     .36   15.21
  175.88  175.88
  175.16  175.16
BR Coef=-1 , 0 , 0 ,, 0 ,,,0.8,-1,,0,
WSPro=,,,, 1 ,,,, 0 ,,,, 0 ,,,,-1 ,-1 ,-1 , 0 , 0 , 0 , 0 , 0
Culvert=2,0.65,2,5.94,0.015,0.2,1,8,1,175,19.5,175.16,7.8,Culvert #1  , 0 ,0.05
    19.5     7.8
BC Culvert Barrel=1,Barrel#1,0
Culvert Bottom n=0.015
BC Design=,, 0 ,, 0 ,,,,,,
BC Use User HTab Curves=0
BC User HTab FreeFlow(D)= 0

Type RM Length L Ch R = 1 ,878.94  ,9.1979,10.5001,13.4581
XS GIS Cut Line= 3
      1135345.57      1696339.27      1135343.85      1696346.89
      1135339.26       1696367.2
#Sta/Elev= 29
       0175.8449    .011 175.844     .16 175.841   .3591175.8019   .5191175.8041
  4.6961175.5941  4.7531175.5861  4.7549175.5861  4.7591175.5849   4.778175.5932
  6.3301175.2789  6.8531175.1741  6.8601 175.157   7.606175.1561  8.7941175.1561
   8.802175.1719  8.9651 175.267  9.7579 175.726  9.8069175.7169  9.8091175.7141
    9.81175.7181   9.817 175.726 12.9229175.7169 13.4981175.7172 14.0269175.7361
 15.2421175.8489 22.9709175.8909 28.0129 175.919 28.6411 175.919
#Mann= 3 , 0 , 0
       0     .02       0   .5191     .03       0  9.7579     .02       0
Bank Sta=0.5191,9.7579
XS Rating Curve= 0 ,0
Exp/Cntr=0.3,0.1

Type RM Length L Ch R = 1 ,868.44  ,7.346,7.1,6.894
XS GIS Cut Line= 3
      1135345.79      1696338.92       1135353.3      1696342.47
       1135378.6      1696354.47
#Sta/Elev= 28
       0175.8891    .349175.9159   2.759175.8699  3.8929 175.801  4.5821 175.765
  4.8991175.7169  5.7001175.5761  6.0341175.5051   6.068175.5051   6.644 175.431
  6.9409175.2499  8.2211175.2521  8.2241175.2521  8.3021175.2469   9.721175.1552
   9.732175.1552   9.981175.8199 10.0011 175.837 13.9501  175.88 14.0101175.8931
 14.1939175.8979  19.193175.9927 21.7261176.1037   24.94175.9998 28.9341175.8855
 30.6629175.9787 34.6801 175.904 36.3069 175.759
#Mann= 3 , 0 , 0
       0     .02       0   2.759     .03       0 13.9501     .02       0
Bank Sta=2.759,13.9501
XS Rating Curve= 0 ,0
Exp/Cntr=0.3,0.1

Type RM Length L Ch R = 2 ,868.39  ,,,
BEGIN DESCRIPTION:
Carrera 15
END DESCRIPTION:
Bridge Culvert--1,0,-1,-1, 0
Deck Dist Width WeirC Skew NumUp NumDn MinLoCord MaxHiCord MaxSubmerge Is_Ogee
0.05,6.95,1.4,0, 2, 2, , , 0.98, 0, 0,0,,
    2.71   21.73
  176.09  176.09
   175.1   175.1
    9.31   21.73
  176.11  176.11
  175.21  175.21
BR Coef=-1 , 0 , 0 ,, 0 ,,,0.8,-1,,0,
WSPro=,,,, 1 ,,,, 0 ,,,, 0 ,,,,-1 ,-1 ,-1 , 0 , 0 , 0 , 0 , 0
Culvert=2,0.59,3,6.95,0.015,0.2,1,8,1,175.25,8.3,175.21,13.4,Culvert #1  , 0 ,0.05
     8.3    13.4
BC Culvert Barrel=1,Barrel#1,0
Culvert Bottom n=0.015
BC Design=,, 0 ,, 0 ,,,,,,
BC Use User HTab Curves=0
BC User HTab FreeFlow(D)= 0

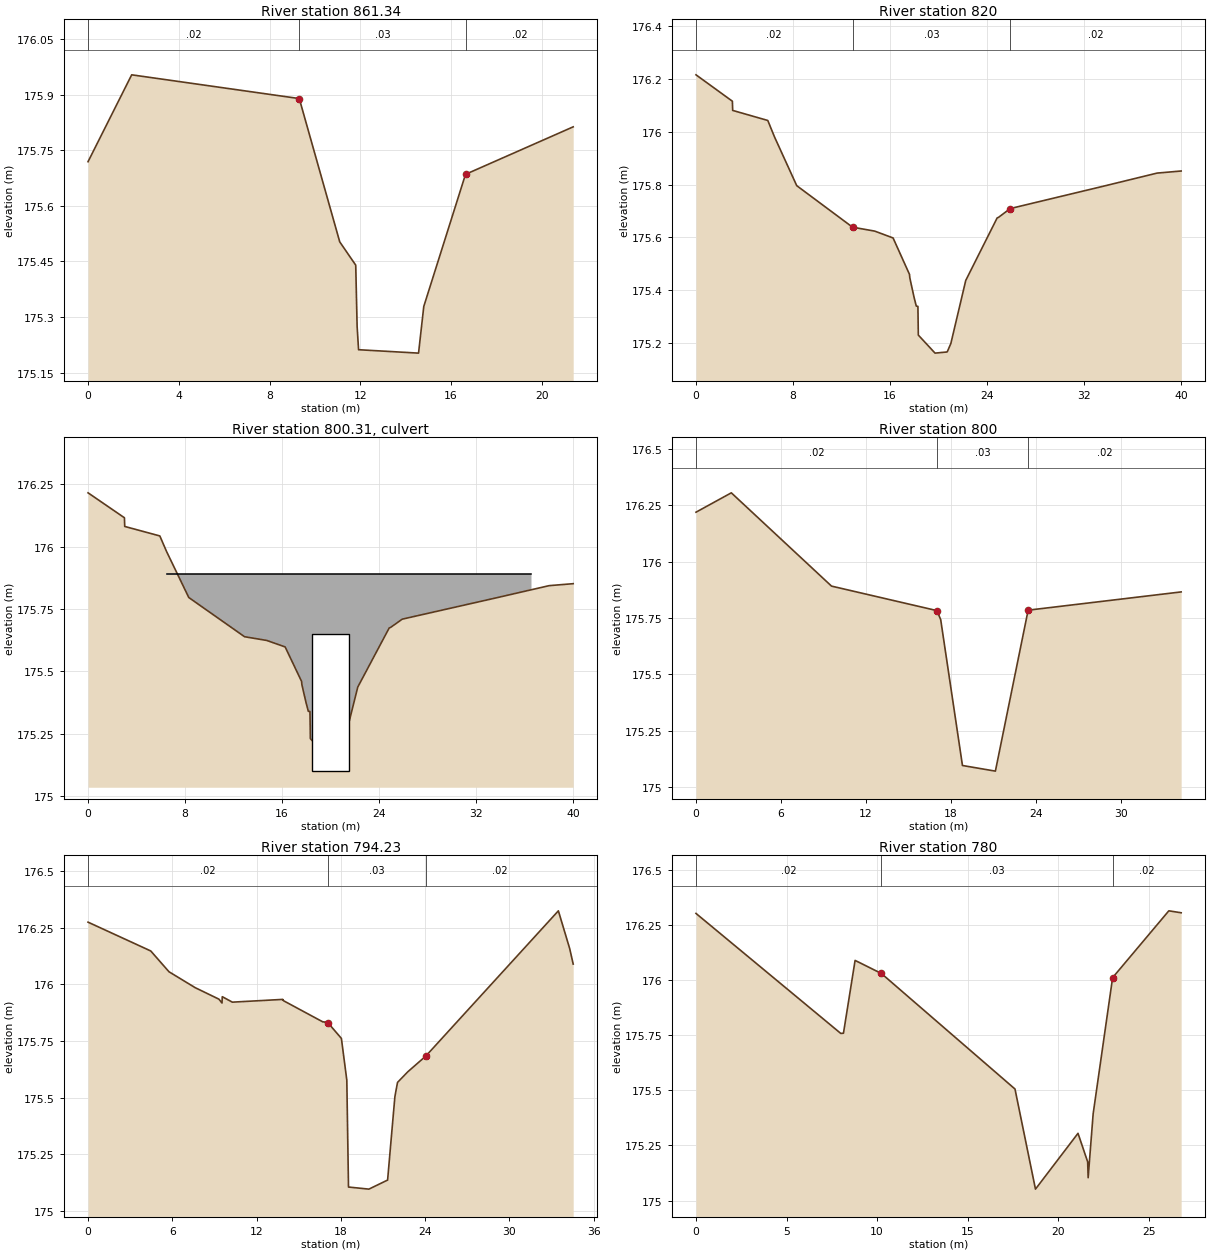
Type RM Length L Ch R = 1 ,861.34  ,43.071,41.3401,39.777
XS GIS Cut Line= 3
       1135347.5      1696332.01        1135359.      1696338.26
1135366.223381671696342.33481843
#Sta/Elev= 11
       0 175.719   1.923175.9531   9.308175.8891 11.0911175.5029 11.7961175.4401
  11.857175.2749  11.921175.2122  14.564 175.203  14.795175.3289 16.6339175.6849
  21.379175.8129
#Mann= 3 , 0 , 0
       0     .02       0   9.308     .03       0 16.6339     .02       0
Bank Sta=9.308,16.6339
XS Rating Curve= 0 ,0
Exp/Cntr=0.3,0.1

Type RM Length L Ch R = 1 ,820     ,20.8669,20.0001,19.8629
XS GIS Cut Line= 3
      1135397.53      1696312.84      1135399.52      1696332.74
      1135401.51      1696352.64
#Sta/Elev= 29
       0176.2159  3.0001176.1159  3.0239176.0811  5.9189 176.043  6.4709175.9809
  8.3049175.7961  12.904175.6389  14.738175.6239 16.2489 175.598 17.6031175.4599
 17.6251175.4481 17.7601175.4191 17.9798175.3731 18.1621175.3399 18.2959175.3389
 18.3301175.2301 19.7081175.1618 20.0001175.1631 20.6849175.1661 20.7179 175.167
 21.0111175.1981   22.24175.4371 22.3601175.4481  24.829175.6739  24.943175.6761
  25.905175.7093   33.56175.7937 38.0159175.8437 40.0001175.8516
#Mann= 3 , 0 , 0
       0     .02       0  12.904     .03       0  25.905     .02       0
Bank Sta=12.904,25.905
XS Rating Curve= 0 ,0
Exp/Cntr=0.3,0.1

Type RM Length L Ch R = 2 ,800.31  ,,,
BEGIN DESCRIPTION:
Carrera 8A
END DESCRIPTION:
Bridge Culvert--1,0,-1,-1, 0
Deck Dist Width WeirC Skew NumUp NumDn MinLoCord MaxHiCord MaxSubmerge Is_Ogee
0.05,6.09,1.4,0, 2, 2, , , 0.98, 0, 0,0,,
    6.47   36.56
  175.89  175.89
   175.1   175.1
   17.01    23.3
  175.92  175.92
   175.1   175.1
BR Coef=-1 , 0 , 0 ,, 0 ,,,0.8,-1,,0,
WSPro=,,,, 1 ,,,, 0 ,,,, 0 ,,,,-1 ,-1 ,-1 , 0 , 0 , 0 , 0 , 0
Culvert=2,0.55,3,6.09,0.015,0.2,1,8,1,175.1,20,175.1,20,Culvert #1  , 0 ,0.05
      20      20
BC Culvert Barrel=1,Barrel#1,0
Culvert Bottom n=0.015
BC Design=,, 0 ,, 0 ,,,,,,
BC Use User HTab Curves=0
BC User HTab FreeFlow(D)= 0

Type RM Length L Ch R = 1 ,800     ,5.7659,5.7699,5.7851
XS GIS Cut Line= 3
      1135422.74      1696312.81      1135419.44      1696332.54
1135417.082020211696346.58814547
#Sta/Elev= 9
       0176.2201   2.493176.3061  9.5661175.8918 17.0069 175.783 17.2739175.7431
 18.8101175.0951 21.1351175.0701  23.447175.7849 34.2489 175.866
#Mann= 3 , 0 , 0
       0     .02       0 17.0069     .03       0  23.447     .02       0
Bank Sta=17.0069,23.447
XS Rating Curve= 0 ,0
Exp/Cntr=0.3,0.1

Type RM Length L Ch R = 1 ,794.23  ,14.183,14.2299,14.496
XS GIS Cut Line= 3
      1135428.42      1696313.76      1135425.12      1696333.49
1135422.719526941696347.83464506
#Sta/Elev= 30
       0 176.275   4.465176.1479   5.765176.0561  7.6279 175.986  9.3229175.9351
  9.5399175.9181  9.5579175.9461  10.276 175.922  13.794175.9339  13.869 175.933
 13.8699175.9339 13.9269175.9281 16.7201175.8349  16.796175.8349  17.099  175.83
  18.042 175.762 18.4279175.5779   18.52175.2149  18.548175.1061 20.0001175.0969
  21.333175.1369    21.6 175.327 21.8511175.5042 21.9362 175.534  22.041175.5679
  22.778175.6151  24.053 175.684 33.4939 176.325 34.3019176.1579   34.55  176.09
#Mann= 3 , 0 , 0
       0     .02       0  17.099     .03       0  24.053     .02       0
Bank Sta=17.099,24.053
XS Rating Curve= 0 ,0
Exp/Cntr=0.3,0.1

Type RM Length L Ch R = 1 ,780     ,20.14,20.0001,19.9229
XS GIS Cut Line= 3
       1135441.4       1696314.9      1135439.28      1696334.79
1135438.557526181696341.53308895
#Sta/Elev= 14
       0176.3021   7.994 175.758  8.1421 175.759   8.784176.0891 10.2349176.0299
 17.6129 175.506  18.744175.0521 21.0919175.3051 21.6259175.1759  21.653175.1039
 21.9279175.3929 23.0039 176.011  26.107176.3139  26.788176.3051
#Mann= 3 , 0 , 0
       0     .02       0 10.2349     .03       0 23.0039     .02       0
Bank Sta=10.2349,23.0039
XS Rating Curve= 0 ,0
Exp/Cntr=0.3,0.1

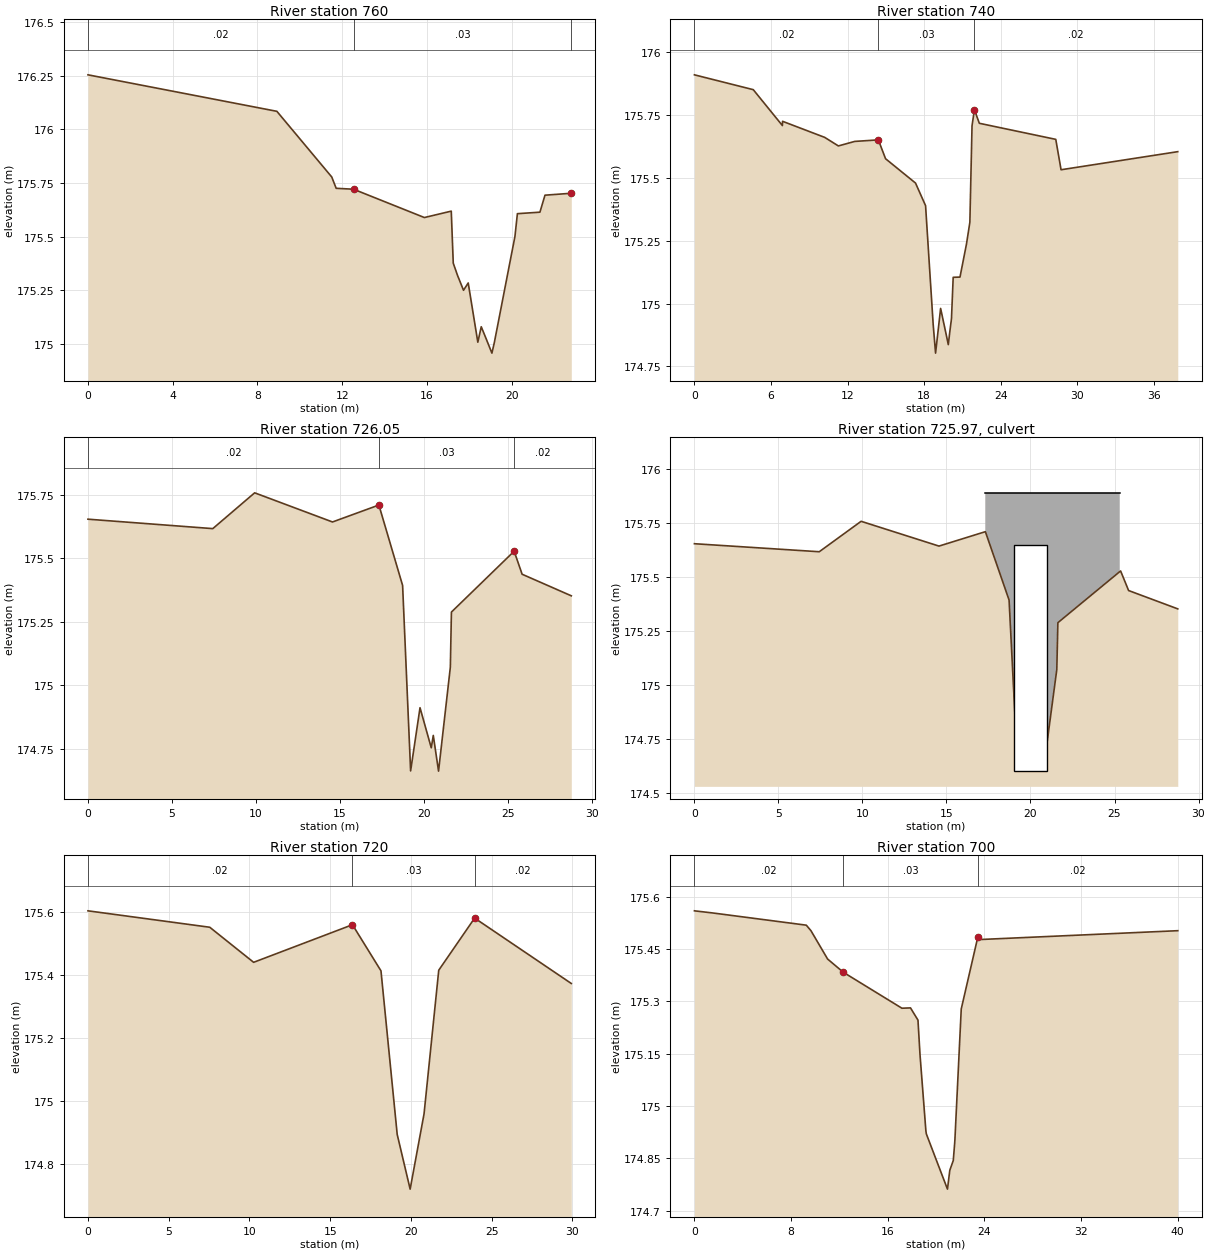
Type RM Length L Ch R = 1 ,760     ,19.972,20.0001,20.0312
XS GIS Cut Line= 3
      1135462.03      1696317.34      1135459.13      1696337.13
 1135458.72309981696339.91635122
#Sta/Elev= 23
       0 176.254  8.9181176.0839 11.5089175.7778 11.7171175.7251 12.5361175.7209
  15.881175.5889 17.1499175.6187 17.2441175.3761  17.462175.3149   17.48175.3109
 17.7281175.2499   17.95175.2841 18.4041175.0079 18.5651175.0799  18.744175.0369
 19.0689 174.957 19.1829175.0061 20.0001175.4218 20.1549175.4999 20.2719175.6069
 21.3351175.6139  21.574175.6931 22.8161 175.702
#Mann= 3 , 0 , 0
       0     .02       0 12.5361     .03       0 22.8161     .02       0
Bank Sta=12.5361,22.8161
XS Rating Curve= 0 ,0
Exp/Cntr=0.3,0.1

Type RM Length L Ch R = 1 ,740     ,14.799,13.9501,13.9141
XS GIS Cut Line= 3
      1135481.53      1696319.98      1135478.95      1696339.82
1135476.651204171696357.55740127
#Sta/Elev= 30
       0 175.911  4.6131175.8519   6.897 175.709   6.908 175.726  10.212 175.662
 11.2861175.6279 12.5651175.6459  14.418 175.652 14.9831 175.577 17.3331175.4801
 18.1201175.3902 18.7169174.9171  18.904174.8031 19.2999174.9811 19.7419174.8759
  19.901174.8369 20.0001 174.879 20.0199174.8882 20.1509  174.94  20.285175.1049
 20.8181175.1058 21.3259175.2371 21.5929 175.324 21.7621175.7081 21.8401175.7349
 21.9499175.7721 22.3339175.7181 28.3269175.6541 28.7411175.5331   37.89175.6051
#Mann= 3 , 0 , 0
       0     .02       0  14.418     .03       0 21.9499     .02       0
Bank Sta=14.418,21.9499
XS Rating Curve= 0 ,0
Exp/Cntr=0.3,0.1

Type RM Length L Ch R = 1 ,726.05  ,6.5889,6.05,6.495
XS GIS Cut Line= 3
      1135497.91      1696322.42      1135492.75      1696341.74
 1135490.49407381696350.20300857
#Sta/Elev= 16
       0175.6541  7.4289175.6169    9.92 175.758 14.5539175.6431 17.3139175.7099
 18.7251175.3929 19.2021 174.662 19.7611 174.911 20.4301174.7531 20.5511174.8019
 20.8639174.6611 21.5661 175.071 21.6301 175.288  25.363175.5279 25.8379175.4371
  28.764175.3521
#Mann= 3 , 0 , 0
       0     .02       0 17.3139     .03       0  25.363     .02       0
Bank Sta=17.3139,25.363
XS Rating Curve= 0 ,0
Exp/Cntr=0.3,0.1

Type RM Length L Ch R = 2 ,725.97  ,,,
BEGIN DESCRIPTION:
Carrera 8
END DESCRIPTION:
Bridge Culvert--1,0,-1,-1, 0
Deck Dist Width WeirC Skew NumUp NumDn MinLoCord MaxHiCord MaxSubmerge Is_Ogee
0.05,5.2,1.4,0, 2, 2, , , 0.98, 0, 0,0,,
   17.31   25.31
  175.89  175.89
   174.6   174.6
   16.38   23.94
  175.91  175.91
  174.72  174.72
BR Coef=-1 , 0 , 0 ,, 0 ,,,0.8,-1,,0,
WSPro=,,,, 1 ,,,, 0 ,,,, 0 ,,,,-1 ,-1 ,-1 , 0 , 0 , 0 , 0 , 0
Culvert=2,1.05,2,5.2,0.015,0.2,1,8,1,174.6,20,174.72,20,Culvert #1  , 0 ,0.05
      20      20
BC Culvert Barrel=1,Barrel#1,0
Culvert Bottom n=0.015
BC Design=,, 0 ,, 0 ,,,,,,
BC Use User HTab Curves=0
BC User HTab FreeFlow(D)= 0

Type RM Length L Ch R = 1 ,720     ,19.8269,20.0001,20.1531
XS GIS Cut Line= 3
      1135503.76      1696323.98       1135498.6       1696343.3
1135496.043241951696352.89653072
#Sta/Elev= 11
       0 175.603   7.542 175.551  10.258  175.44  16.377 175.559  18.143 175.413
  19.148 174.895  19.949 174.722  20.809  174.96   21.72 175.415  23.942  175.58
  29.927 175.373
#Mann= 3 , 0 , 0
       0     .02       0  16.377     .03       0  23.942     .02       0
Bank Sta=16.377,23.942
XS Rating Curve= 0 ,0
Exp/Cntr=0.3,0.1

Type RM Length L Ch R = 1 ,700     ,19.9979,20.0001,20.0049
XS GIS Cut Line= 3
      1135521.65      1696326.98      1135518.31      1696346.69
      1135514.98      1696366.41
#Sta/Elev= 24
       0 175.559    1.51175.5529  9.2589175.5179   9.646 175.502 11.0231175.4209
   12.32175.3831 17.1709175.2801  17.882 175.281 18.5011 175.246 18.6669175.1481
 19.1549 174.929  19.193174.9202 20.0001 174.847  20.941 174.762 21.1339174.8159
  21.422174.8439  21.539174.8939 21.5579 174.904 22.0821 175.278  23.448175.4831
 23.6019175.4819 23.6031 175.481  23.761 175.477 40.0001175.5021
#Mann= 3 , 0 , 0
       0     .02       0   12.32     .03       0  23.448     .02       0
Bank Sta=12.32,23.448
XS Rating Curve= 0 ,0
Exp/Cntr=0.3,0.1

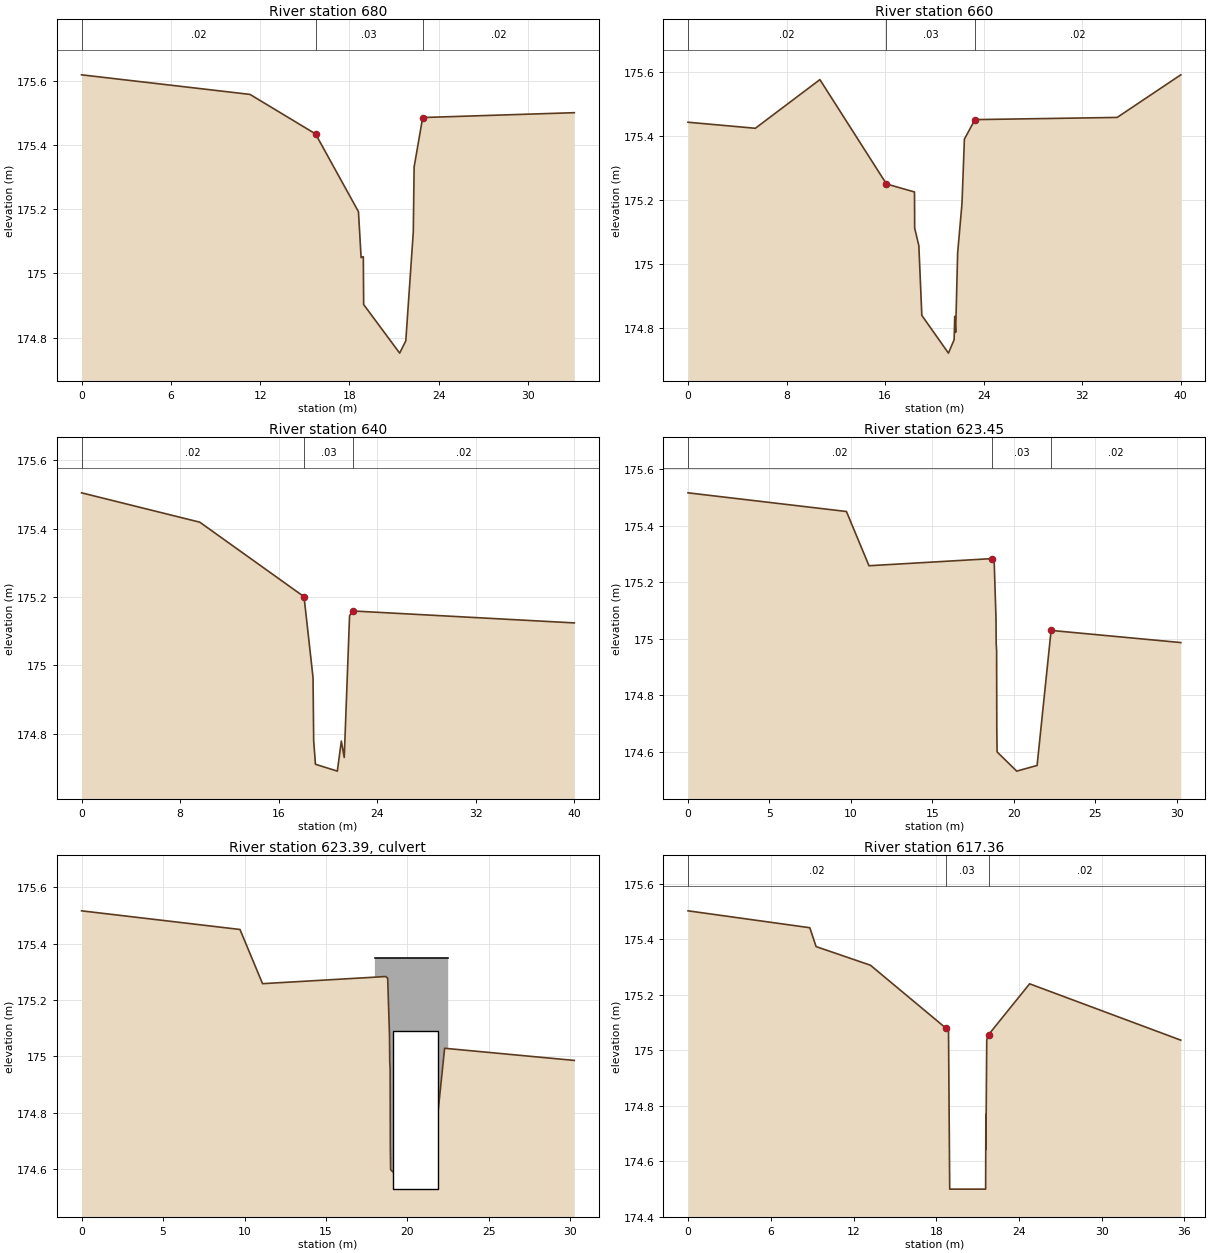
Type RM Length L Ch R = 1 ,680     ,20.0211,20.0001,19.979
XS GIS Cut Line= 3
      1135541.38      1696330.06      1135538.07      1696349.78
1135535.90072978 1696362.7038697
#Sta/Elev= 13
       0175.6178 11.3169175.5569  15.721 175.434 18.6059 175.192  18.783175.0491
  18.932175.0521 18.9549174.9031  21.375174.7519 21.7859  174.79   22.29175.1289
 22.3461 175.331  22.921175.4849 33.1089   175.5
#Mann= 3 , 0 , 0
       0     .02       0  15.721     .03       0  22.921     .02       0
Bank Sta=15.721,22.921
XS Rating Curve= 0 ,0
Exp/Cntr=0.3,0.1

Type RM Length L Ch R = 1 ,660     ,20.0001,20.0001,20.001
XS GIS Cut Line= 3
      1135561.31      1696333.49      1135557.78      1696353.17
      1135554.25      1696372.86
#Sta/Elev= 18
       0175.4429   5.466 175.424 10.7061175.5761  16.109175.2499 18.3849175.2249
 18.3989175.1119 18.7379 175.057 18.9799174.8391   21.14174.7211 21.6009174.7629
 21.6509 174.836 21.7231 174.786 21.8871175.0341   22.24 175.189 22.4351175.3902
  23.295175.4511 34.8371175.4579 40.0001175.5911
#Mann= 3 , 0 , 0
       0     .02       0  16.109     .03       0  23.295     .02       0
Bank Sta=16.109,23.295
XS Rating Curve= 0 ,0
Exp/Cntr=0.3,0.1

Type RM Length L Ch R = 1 ,640     ,16.9341,16.55,16.661
XS GIS Cut Line= 3
        1135581.      1696337.02      1135577.47      1696356.71
      1135573.93      1696376.39
#Sta/Elev= 12
       0175.5051  9.5991175.4191 18.0591175.2009 18.7909 174.964  18.843 174.779
 18.9869174.7101 20.7621  174.69   21.09174.7781  21.325174.7299 21.7569175.1451
  22.027175.1591 40.0001175.1241
#Mann= 3 , 0 , 0
       0     .02       0 18.0591     .03       0  22.027     .02       0
Bank Sta=18.0591,22.027
XS Rating Curve= 0 ,0
Exp/Cntr=0.3,0.1

Type RM Length L Ch R = 1 ,623.45  ,6.1131,6.0899,6.103
XS GIS Cut Line= 3
      1135597.82      1696339.93      1135593.77      1696359.52
1135591.69622161 1696369.5509429
#Sta/Elev= 14
       0 175.516  9.7219175.4499 11.1069175.2579 18.6641175.2832  18.786175.2771
 18.8991175.0728 18.9119174.9811 18.9369174.9579 18.9491 174.676 18.9671174.5989
 20.1701174.5309  21.422 174.551 22.2809 175.029 30.2389 174.986
#Mann= 3 , 0 , 0
       0     .02       0 18.6641     .03       0 22.2809     .02       0
Bank Sta=18.6641,22.2809
XS Rating Curve= 0 ,0
Exp/Cntr=0.3,0.1

Type RM Length L Ch R = 2 ,623.39  ,,,
BEGIN DESCRIPTION:
Carrera 7A
END DESCRIPTION:
Bridge Culvert--1,0,-1,-1, 0
Deck Dist Width WeirC Skew NumUp NumDn MinLoCord MaxHiCord MaxSubmerge Is_Ogee
0.05,6,1.4,0, 2, 2, , , 0.98, 0, 0,0,,
      18    22.5
  175.35  175.35
  174.53  174.53
      18    24.8
  175.31  175.31
  174.49  174.49
BR Coef=-1 , 0 , 0 ,, 0 ,,,0.8,-1,,0,
WSPro=,,,, 1 ,,,, 0 ,,,, 0 ,,,,-1 ,-1 ,-1 , 0 , 0 , 0 , 0 , 0
Culvert=2,0.56,2.8,6,0.015,0.2,1,8,1,174.53,20.5,174.49,20.3,Culvert #1  , 0 ,0.05
    20.5    20.3
BC Culvert Barrel=1,Barrel#1,0
Culvert Bottom n=0.015
BC Design=,, 0 ,, 0 ,,,,,,
BC Use User HTab Curves=0
BC User HTab FreeFlow(D)= 0

Type RM Length L Ch R = 1 ,617.36  ,17.0929,17.3599,17.7701
XS GIS Cut Line= 3
      1135603.79      1696341.17      1135599.74      1696360.75
1135596.554106151696376.16028656
#Sta/Elev= 14
       0175.5029  8.8319 175.442  9.2879 175.374 13.2289175.3069   18.68175.0811
 18.8891175.0741 18.9759174.5001 21.5811174.5001 21.5981 174.769    21.6174.6431
 21.6621175.0381 21.7999 175.057 24.7699175.2399  35.732175.0369
#Mann= 3 , 0 , 0
       0     .02       0   18.68     .03       0 21.7999     .02       0
Bank Sta=18.68,21.7999
XS Rating Curve= 0 ,0
Exp/Cntr=0.3,0.1

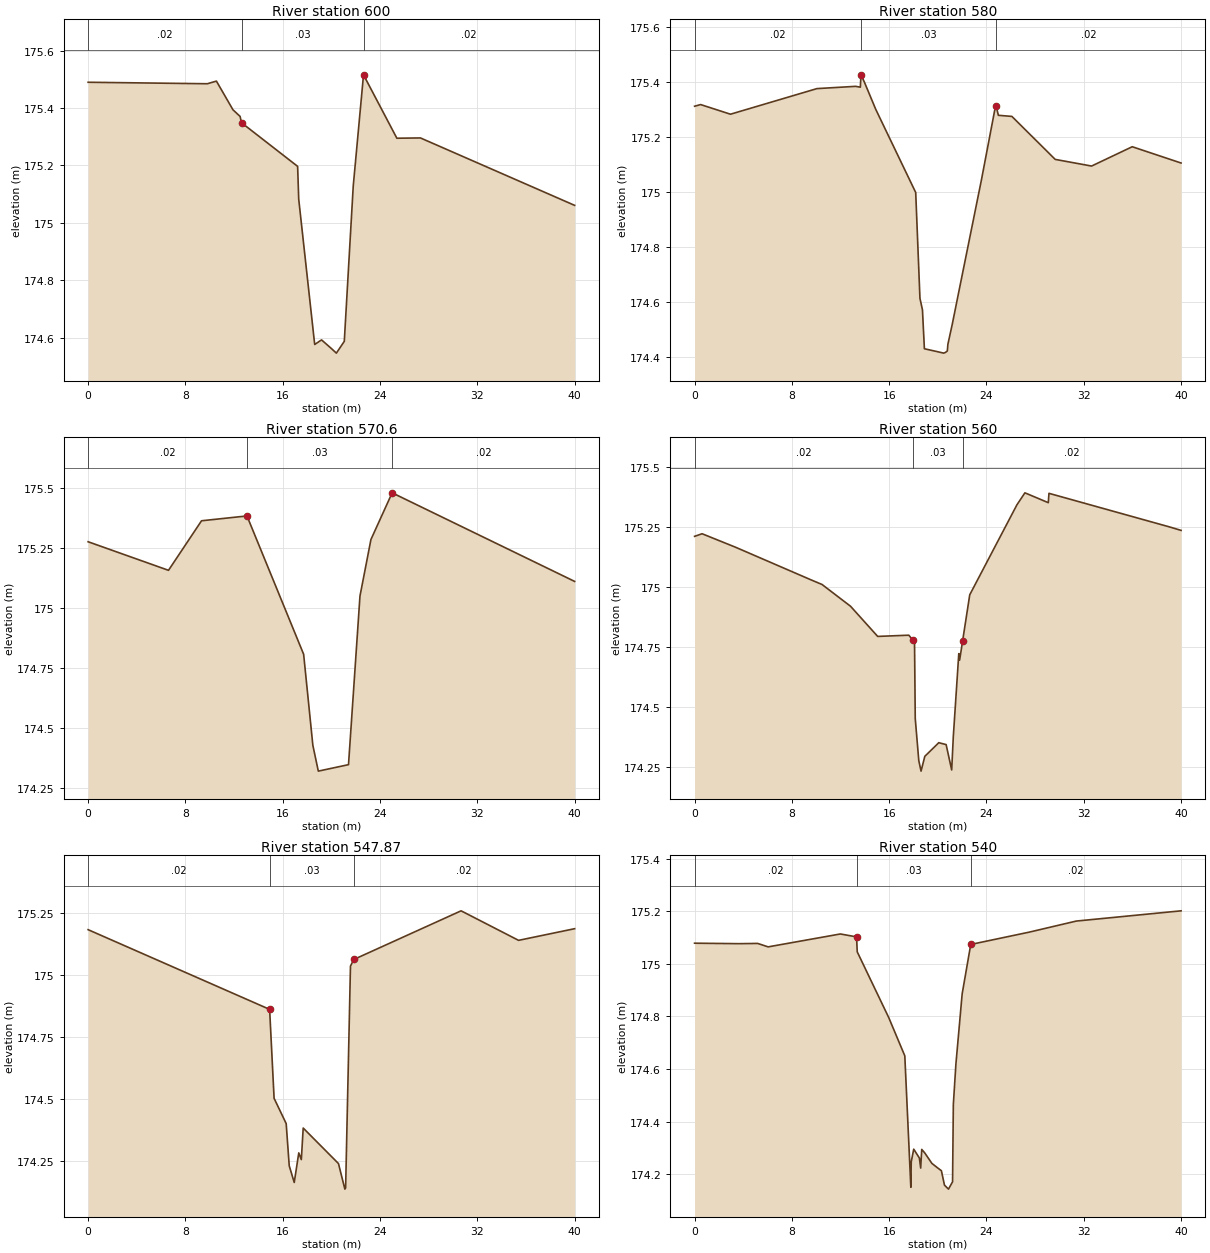
Type RM Length L Ch R = 1 ,600     ,20.068,20.0001,19.9571
XS GIS Cut Line= 3
      1135616.77      1696340.83      1135617.06      1696360.82
      1135617.36      1696380.82
#Sta/Elev= 20
       0175.4901   9.803175.4849 10.5491175.4941 11.9101175.3941 12.4959 175.371
 12.6111 175.349 17.2261175.1969 17.3151175.0829 18.6291 174.576 19.1201174.5901
  19.196174.5919 20.0001 174.562 20.4109174.5459 21.0629 174.587 21.6399175.0119
 21.7981 175.128  22.643 175.516  25.385 175.295 27.3241 175.296 40.0001 175.061
#Mann= 3 , 0 , 0
       0     .02       0 12.6111     .03       0  22.643     .02       0
Bank Sta=12.6111,22.643
XS Rating Curve= 0 ,0
Exp/Cntr=0.3,0.1

Type RM Length L Ch R = 1 ,580     ,9.3949,9.4,9.4491
XS GIS Cut Line= 3
      1135637.45      1696340.67      1135637.06      1696360.67
      1135636.68      1696380.66
#Sta/Elev= 30
       0175.3109   .4959 175.317   2.952 175.282 10.0599175.3749  13.235175.3831
 13.6291175.3801 13.6809175.4249 13.9559 175.399 14.9029 175.299  18.181174.9979
   18.48 174.669 18.5291174.6141 18.7361174.5721 18.8949 174.431 20.0001  174.42
 20.4829174.4151 20.6429174.4181 20.7819 174.423 20.8261174.4471  21.187  174.52
 21.5201174.5931  23.586175.0439  24.701175.3021 24.7869 175.313 24.9759 175.278
 26.0891 175.274 29.6519 175.118 32.6419175.0939 35.9841 175.164 40.0001175.1049
#Mann= 3 , 0 , 0
       0     .02       0 13.6809     .03       0 24.7869     .02       0
Bank Sta=13.6809,24.7869
XS Rating Curve= 0 ,0
Exp/Cntr=0.3,0.1

Type RM Length L Ch R = 1 ,570.6   ,10.1209,10.6,11.07
XS GIS Cut Line= 3
      1135647.72      1696342.55      1135646.25       1696362.5
      1135644.77      1696382.44
#Sta/Elev= 12
       0175.2758   6.609 175.157  9.3251 175.363 13.0619175.3831 17.7199 174.808
 18.4791174.4291 18.9269174.3221 21.4092 174.349 22.3519  175.05 23.2529 175.285
 24.9979175.4792 40.0001175.1109
#Mann= 3 , 0 , 0
       0     .02       0 13.0619     .03       0 24.9979     .02       0
Bank Sta=13.0619,24.9979
XS Rating Curve= 0 ,0
Exp/Cntr=0.3,0.1

Type RM Length L Ch R = 1 ,560     ,10.996,12.1301,13.2
XS GIS Cut Line= 3
      1135654.13       1696341.8      1135656.79      1696361.62
      1135659.44      1696381.44
#Sta/Elev= 29
       0175.2122   .6169175.2231  3.3549 175.167  9.6381 175.029 10.4809 175.011
 12.8199174.9202  15.055 174.794  17.612174.7991   17.96174.7781 18.0841174.7699
 18.1429174.4511  18.434174.2749 18.6199 174.231 18.9299174.2929 20.0001174.3459
 20.0741174.3499 20.6819174.3419 21.1391174.2359  21.272174.3749 21.7231 174.722
  21.792174.6949 22.0401 174.776 22.6241 174.968 26.5039175.3441 27.1589175.3941
  29.081 175.353 29.1371 175.392 39.0769175.2512 40.0001175.2371
#Mann= 3 , 0 , 0
       0     .02       0   17.96     .03       0 22.0401     .02       0
Bank Sta=17.96,22.0401
XS Rating Curve= 0 ,0
Exp/Cntr=0.3,0.1

Type RM Length L Ch R = 1 ,547.87  ,7.5959,7.8699,8.1119
XS GIS Cut Line= 3
      1135656.23      1696343.52      1135668.59      1696359.24
      1135680.96      1696374.96
#Sta/Elev= 17
       0 175.182 14.9239 174.861 15.2909174.5029 16.2849174.4011  16.536 174.231
 16.9481174.1639   17.32174.2831   17.53 174.256 17.6839174.3831 20.5841174.2401
 21.1101174.1371  21.172 174.142  21.571175.0351 21.8401175.0619 30.6659175.2579
 35.3918 175.139 40.0001175.1859
#Mann= 3 , 0 , 0
       0     .02       0 14.9239     .03       0 21.8401     .02       0
Bank Sta=14.9239,21.8401
XS Rating Curve= 0 ,0
Exp/Cntr=0.3,0.1

Type RM Length L Ch R = 1 ,540     ,21.062,20.0001,19.214
XS GIS Cut Line= 3
      1135659.81      1696339.87      1135674.21      1696353.75
      1135688.61      1696367.63
#Sta/Elev= 30
       0175.0789  3.6451175.0771  5.1871 175.078  6.0481175.0649  11.986 175.114
  13.317 175.103 13.3731 175.046 15.9609174.7961 17.2849174.6501 17.7811174.1499
  17.814174.2471 18.0189 174.295   18.32174.2731 18.4849174.2609 18.5901174.2231
 18.6769174.2941 18.9211 174.281  19.509 174.241 20.0001174.2231  20.293 174.213
  20.545174.1582  20.877174.1429  21.211174.1709  21.275174.4651  21.485174.6181
 21.9999 174.886 22.7061175.0741  27.517 175.121  31.381175.1631 40.0001175.2021
#Mann= 3 , 0 , 0
       0     .02       0  13.317     .03       0 22.7061     .02       0
Bank Sta=13.317,22.7061
XS Rating Curve= 0 ,0
Exp/Cntr=0.3,0.1