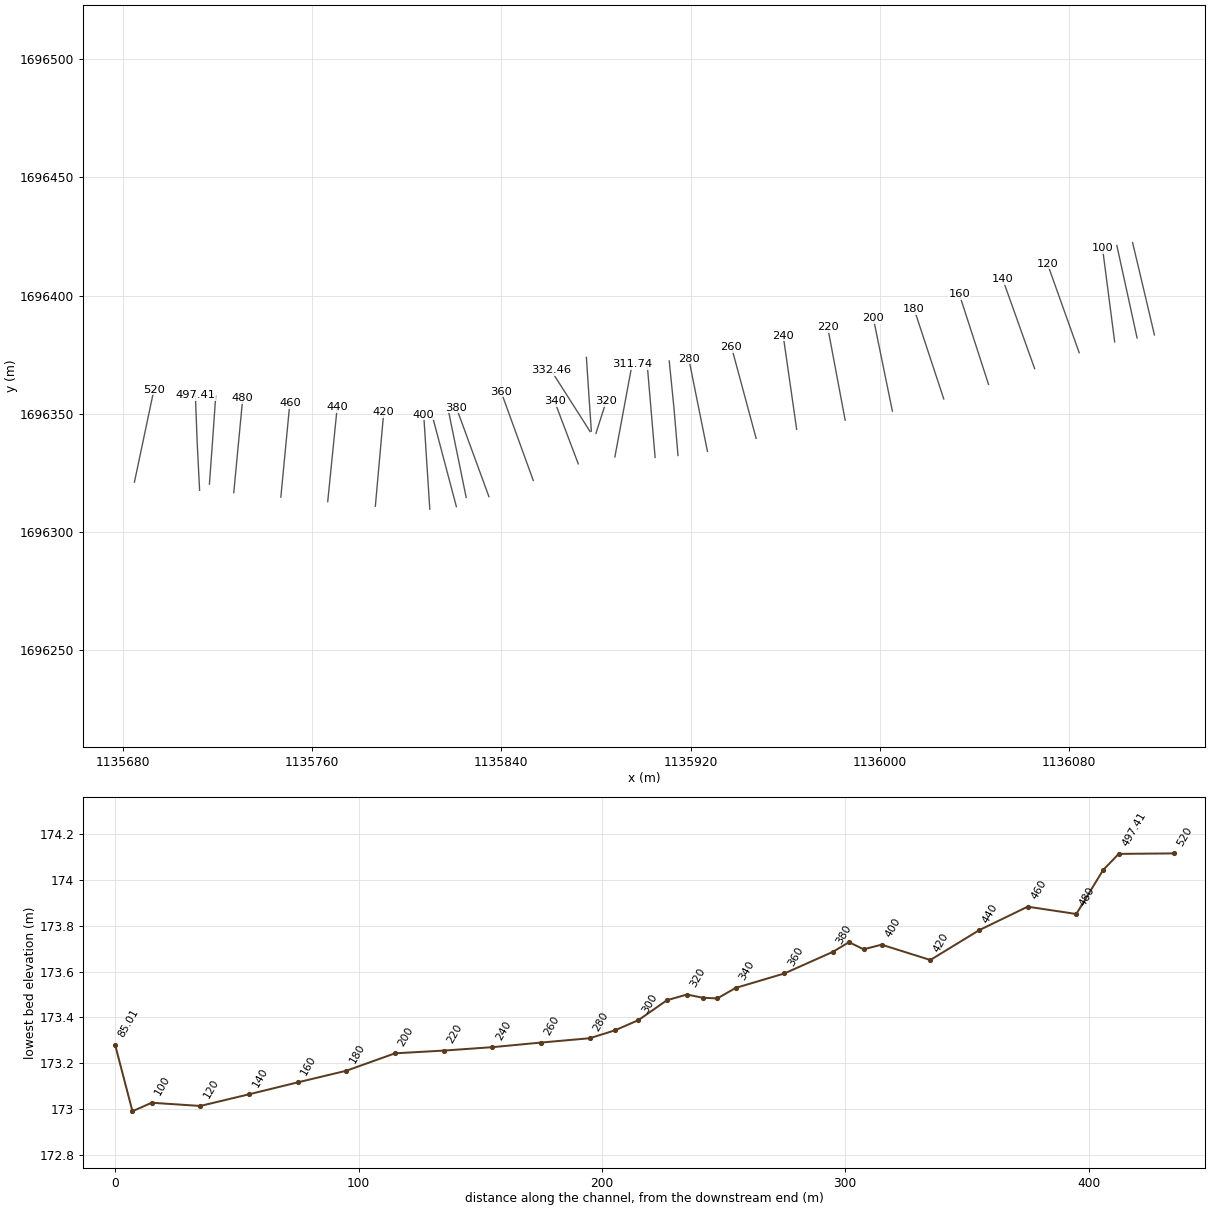
HEC-RAS study AcequiaDiseño.prj: Acequia Diseño

--- AcequiaDiseño.g01 (geometry) --- (continued)

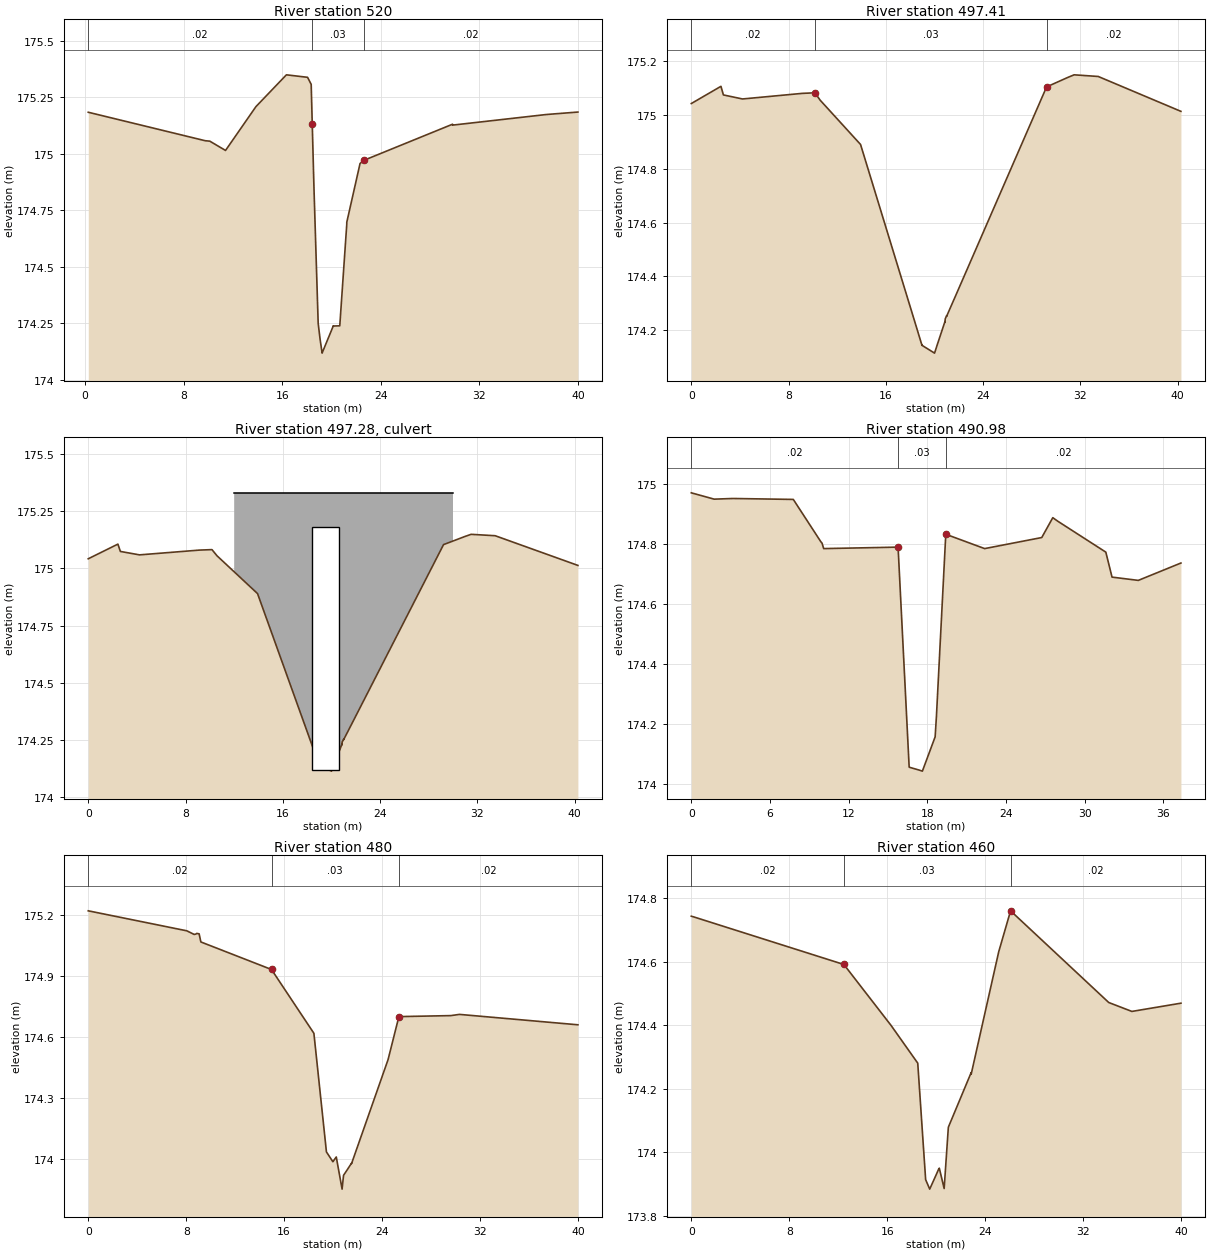
Type RM Length L Ch R = 1 ,520     ,23.0411,22.5899,22.2379
XS GIS Cut Line= 3
      1135684.92      1696321.13      1135689.05       1696340.7
      1135693.18      1696360.27
#Sta/Elev= 28
   .2621175.1841  9.7579175.0579  10.123175.0561  11.402175.0149 13.8711175.2091
 16.3419175.3499   18.06175.3389 18.3541175.3078 18.4401 175.132  18.577174.8531
 18.9211 174.249  19.078 174.178  19.242 174.117 19.2841174.1231 20.0001174.2179
  20.143174.2371 20.1461174.2359  20.154174.2371  20.674 174.238 21.2001 174.655
   21.24174.6861 21.2439 174.697  22.319 174.957 22.6299174.9711 29.8271175.1311
  29.832175.1271 37.4419175.1741 40.0001 175.185
#Mann= 3 , 0 , 0
   .2621     .02       0 18.4401     .03       0 22.6299     .02       0
Bank Sta=18.4401,22.6299
XS Rating Curve= 0 ,0
Exp/Cntr=0.3,0.1

Type RM Length L Ch R = 1 ,497.41  ,6.733,6.4301,6.5989
XS GIS Cut Line= 3
      1135712.47      1696317.71      1135711.45      1696337.84
      1135710.68      1696357.95
#Sta/Elev= 30
       0175.0421  2.4381175.1061  2.6411175.0741  4.2139175.0591  9.1309175.0799
 10.1751 175.082 10.5939175.0549  13.923  174.89  18.366 174.234  18.933174.1499
 18.9589174.1469  18.961 174.145  18.965 174.145 18.9671174.1441 18.9701174.1441
  20.008174.1149 20.0089174.1149  20.147174.1341 20.2171174.1441 20.8629174.2319
 20.8681174.2301 20.8861 174.242 21.0041174.2538 21.0041 174.252  21.749174.3288
 29.2239175.1039 31.0079175.1399 31.4901175.1488 33.4701175.1427 40.2751175.0131
#Mann= 3 , 0 , 0
       0     .02       0 10.1751     .03       0 29.2239     .02       0
Bank Sta=10.1751,29.2239
XS Rating Curve= 0 ,0
Exp/Cntr=0.3,0.1

Type RM Length L Ch R = 2 ,497.28  ,,,
BEGIN DESCRIPTION:
Carrera 6
END DESCRIPTION:
Bridge Culvert--1,0,-1,-1, 0
Deck Dist Width WeirC Skew NumUp NumDn MinLoCord MaxHiCord MaxSubmerge Is_Ogee
0.05,6.33,1.4,0, 2, 2, , , 0.98, 0, 0,0,,
      12      30
  175.33  175.33
  174.12  174.12
    15.5      20
  175.28  175.28
  174.02  174.02
BR Coef=-1 , 0 , 0 ,, 0 ,,,0.8,-1,,0,
WSPro=,,,, 1 ,,,, 0 ,,,, 0 ,,,,-1 ,-1 ,-1 , 0 , 0 , 0 , 0 , 0
Culvert=2,1.06,2.2,6.33,0.15,0.2,1,8,1,174.12,19.5,174.02,17.5,Culvert #1  , 0 ,0.05
    19.5    17.5
BC Culvert Barrel=1,Barrel#1,0
Culvert Bottom n=0.15
BC Design=,, 0 ,, 0 ,,,,,,
BC Use User HTab Curves=0
BC User HTab FreeFlow(D)= 0

Type RM Length L Ch R = 1 ,490.98  ,10.9499,10.9801,11.003
XS GIS Cut Line= 3
      1135716.62      1696320.31      1135717.88      1696337.59
      1135719.28      1696357.57
#Sta/Elev= 25
       0 174.972  1.7441174.9509   3.173174.9531  7.7818  174.95  9.8819174.8089
   9.977 174.804  10.098 174.786  15.774174.7909 16.3601174.2831 16.6189174.0579
 16.6271174.0569 17.3261174.0481 17.6309174.0439 17.6391174.0451  18.601174.1582
 18.7001 174.227  19.413174.8339 22.3769 174.786  26.734174.8229 27.5759174.8891
 27.9709174.8769 31.6221174.7742 32.0951174.6909 34.1001  174.68 37.3511174.7379
#Mann= 3 , 0 , 0
       0     .02       0  15.774     .03       0  19.413     .02       0
Bank Sta=15.774,19.413
XS Rating Curve= 0 ,0
Exp/Cntr=0.3,0.1

Type RM Length L Ch R = 1 ,480     ,20.0001,20.0001,20.001
XS GIS Cut Line= 3
      1135726.91       1696316.7       1135728.8      1696336.61
       1135730.7      1696356.52
#Sta/Elev= 25
       0175.2201   8.047175.1219  8.6581175.1039  8.8011175.1061  8.8599175.1091
  9.0571 175.107   9.197175.0671 14.9699174.9317 18.4319174.6181      19 174.295
 19.4569 174.035  19.983173.9868 20.0001173.9881  20.246174.0091  20.261  174.01
 20.7349173.8521  20.855173.9201 21.1199173.9439  21.511173.9801  21.511 173.978
 24.4919174.4888 25.3761174.7001 29.6101 174.705  30.323 174.711 40.0001174.6599
#Mann= 3 , 0 , 0
       0     .02       0 14.9699     .03       0 25.3761     .02       0
Bank Sta=14.9699,25.3761
XS Rating Curve= 0 ,0
Exp/Cntr=0.3,0.1

Type RM Length L Ch R = 1 ,460     ,19.9949,20.0001,20.0059
XS GIS Cut Line= 3
      1135746.81      1696314.81      1135748.71      1696334.71
      1135750.62      1696354.62
#Sta/Elev= 21
       0 174.744   .1719174.7422  12.466174.5919  16.322174.3998 18.5001 174.281
 18.9601174.0188 19.1451 173.914 19.4761173.8841 20.0001173.9289 20.2189173.9481
 20.2619  173.95 20.6569 173.886 20.9989174.0789   21.04174.0829 22.8621174.2511
  22.863174.2459 25.1149174.6321  26.083 174.761 34.1029174.4721 35.9929 174.444
 40.0001  174.47
#Mann= 3 , 0 , 0
       0     .02       0  12.466     .03       0  26.083     .02       0
Bank Sta=12.466,26.083
XS Rating Curve= 0 ,0
Exp/Cntr=0.3,0.1

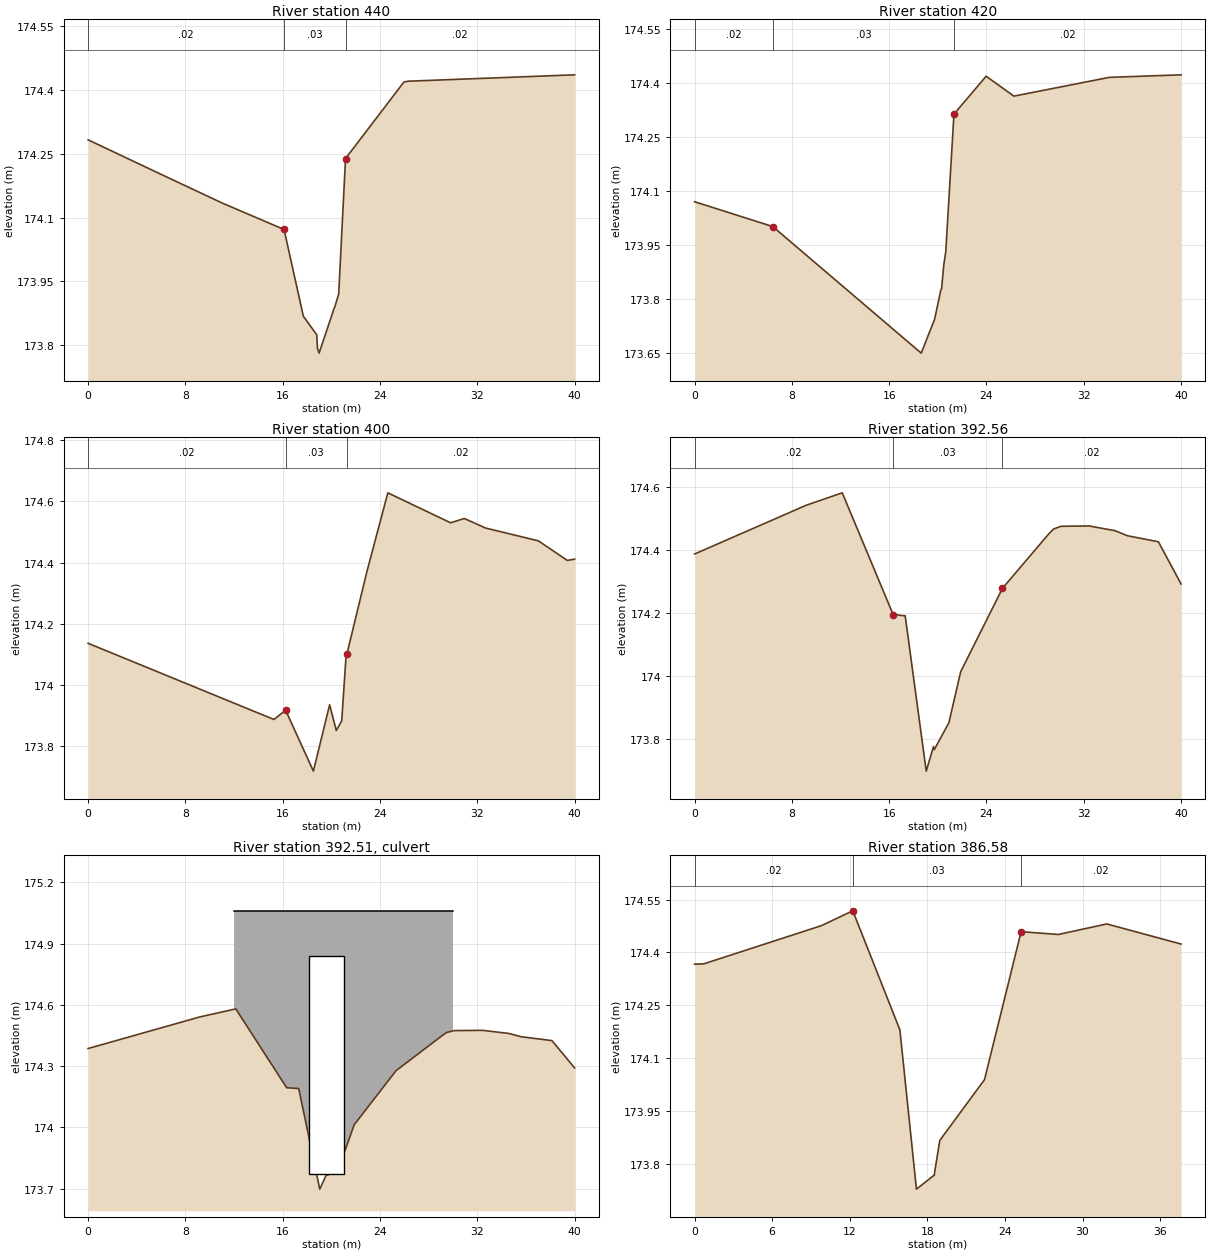
Type RM Length L Ch R = 1 ,440     ,20.0159,20.0001,19.987
XS GIS Cut Line= 3
      1135766.62       1696312.9      1135768.62       1696332.8
      1135770.62       1696352.7
#Sta/Elev= 16
       0 174.283   6.429 174.196  11.044 174.134   16.11 174.072  17.696 173.868
    18.8 173.824  18.855 173.793  18.991 173.781      20 173.867  20.215 173.886
  20.285  173.89  20.602  173.92  21.165 174.239  25.964 174.419  26.311 174.421
      40 174.436
#Mann= 3 , 0 , 0
       0     .02       0   16.11     .03       0  21.165     .02       0
Bank Sta=16.11,21.165
XS Rating Curve= 0 ,0
Exp/Cntr=0.3,0.1

Type RM Length L Ch R = 1 ,420     ,20.239,20.0001,19.809
XS GIS Cut Line= 3
      1135786.75      1696310.97      1135788.53      1696330.89
      1135790.31      1696350.81
#Sta/Elev= 16
       0 174.071  6.4291174.0021 18.5599173.6531 18.6339 173.651  19.737173.7451
 20.0001173.7869 20.2439173.8259 20.3079173.8299 20.4929173.8969 20.6511 173.932
  21.161  174.22 21.3241174.3139 23.9731174.4191 26.2549174.3639 34.1041 174.416
 40.0001 174.423
#Mann= 3 , 0 , 0
       0     .02       0  6.4291     .03       0 21.3241     .02       0
Bank Sta=6.4291,21.3241
XS Rating Curve= 0 ,0
Exp/Cntr=0.3,0.1

Type RM Length L Ch R = 1 ,400     ,7.7291,7.4399,7.0881
XS GIS Cut Line= 3
      1135809.76      1696309.75      1135808.47      1696329.71
      1135807.19      1696349.67
#Sta/Elev= 18
       0174.1359 15.2769173.8869 16.2391173.9171 18.5209 173.718 19.8571 173.935
 20.0001173.9131 20.4051173.8509 20.8529173.8829 21.1949174.0871 21.2799174.1012
   22.92  174.37 24.6431174.6279 29.7979  174.53 30.9329 174.544 32.6691174.5129
  37.018174.4709  39.403174.4069 40.0001174.4111
#Mann= 3 , 0 , 0
       0     .02       0 16.2391     .03       0 21.2799     .02       0
Bank Sta=16.2391,21.2799
XS Rating Curve= 0 ,0
Exp/Cntr=0.3,0.1

Type RM Length L Ch R = 1 ,392.56  ,5.9089,5.9799,6.324
XS GIS Cut Line= 3
        1135821.      1696310.77      1135815.88      1696330.11
      1135810.76      1696349.44
#Sta/Elev= 22
       0174.3861  9.2031 174.541  12.142  174.58  16.326174.1941 17.3169174.1902
   18.68173.8021  19.046173.6979 19.6431173.7759  19.709173.7659 20.0001173.7869
 20.9209173.8521 20.9251 173.854 21.8801174.0131 25.3149174.2773 29.1011174.4489
  29.508174.4651 30.1149174.4739 32.4231174.4751 34.5829174.4599 35.5799 174.444
 38.1341174.4249 40.0001 174.291
#Mann= 3 , 0 , 0
       0     .02       0  16.326     .03       0 25.3149     .02       0
Bank Sta=16.326,25.3149
XS Rating Curve= 0 ,0
Exp/Cntr=0.3,0.1

Type RM Length L Ch R = 2 ,392.51  ,,,
BEGIN DESCRIPTION:
Carrera 5
END DESCRIPTION:
Bridge Culvert--1,0,-1,-1, 0
Deck Dist Width WeirC Skew NumUp NumDn MinLoCord MaxHiCord MaxSubmerge Is_Ogee
0.05,5.8,1.4,0, 2, 2, , , 0.98, 0, 0,0,,
      12      30
  175.06  175.06
  173.77  173.77
      12    25.5
  175.06  175.06
  173.77  173.77
BR Coef=-1 , 0 , 0 ,, 0 ,,,0.8,-1,,0,
WSPro=,,,, 1 ,,,, 0 ,,,, 0 ,,,,-1 ,-1 ,-1 , 0 , 0 , 0 , 0 , 0
Culvert=2,1.07,2.8,5.8,0.015,0.2,1,8,1,173.77,19.6,173.77,18,Culvert #1  , 0 ,0.05
    19.6      18
BC Culvert Barrel=1,Barrel#1,0
Culvert Bottom n=0.015
BC Design=,, 0 ,, 0 ,,,,,,
BC Use User HTab Curves=0
BC User HTab FreeFlow(D)= 0

Type RM Length L Ch R = 1 ,386.58  ,6.815,6.58,6.434
XS GIS Cut Line= 3
      1135825.14      1696314.66      1135821.67      1696331.64
       1135817.6      1696351.52
#Sta/Elev= 18
       0174.3669   .7169174.3678  9.8021 174.476 12.2359174.5181  15.764174.1911
 15.8609174.1819 15.8731174.1819 17.1569 173.729   17.33173.7339 18.5379173.7689
  18.541173.7689 18.5641173.7768 18.9619173.8671  22.419174.0393  25.253 174.459
  28.134174.4511  31.879174.4809  37.623174.4239
#Mann= 3 , 0 , 0
       0     .02       0 12.2359     .03       0  25.253     .02       0
Bank Sta=12.2359,25.253
XS Rating Curve= 0 ,0
Exp/Cntr=0.3,0.1

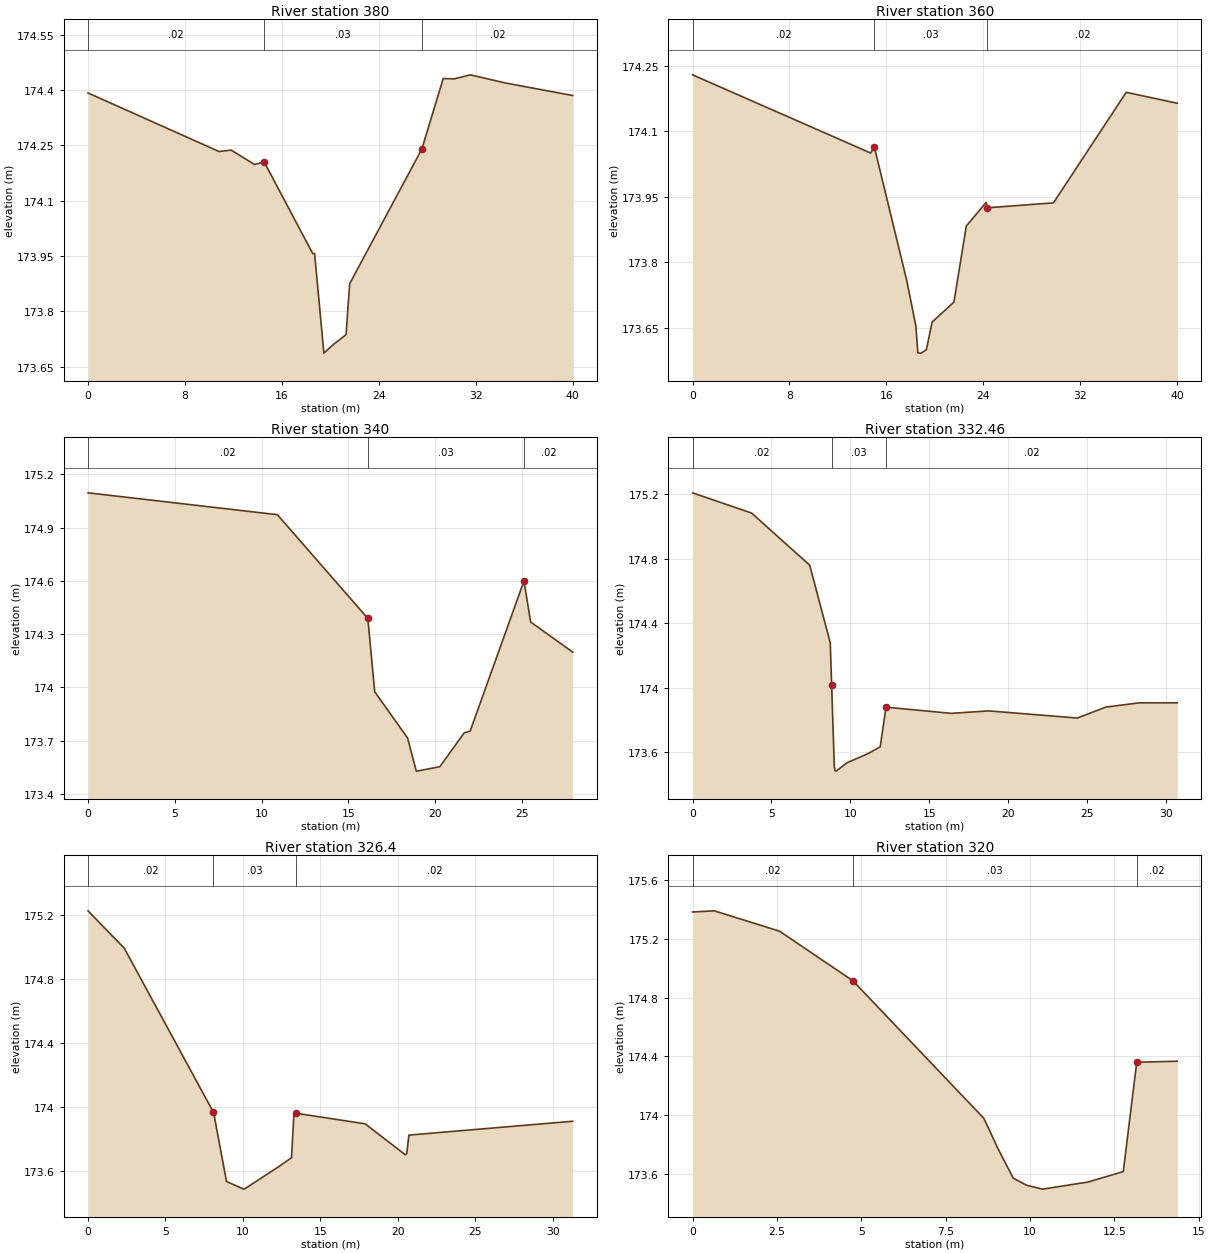
Type RM Length L Ch R = 1 ,380     ,20.0119,20.0001,20.0159
XS GIS Cut Line= 3
      1135834.75      1696315.02      1135827.87      1696333.81
        1135821.      1696352.59
#Sta/Elev= 20
       0174.3919 10.8189174.2331 11.8101174.2371 13.7389174.1981 14.5359174.2051
 18.1999 173.978  18.541 173.957 18.6961 173.957 19.4639173.6869 20.0001173.7031
  20.311173.7119 21.2921173.7369 21.5929 173.875 21.9999   173.9 27.5509174.2401
 29.3111 174.431 30.2099  174.43  31.548 174.441 34.4101174.4191 40.0001174.3849
#Mann= 3 , 0 , 0
       0     .02       0 14.5359     .03       0 27.5509     .02       0
Bank Sta=14.5359,27.5509
XS Rating Curve= 0 ,0
Exp/Cntr=0.3,0.1

Type RM Length L Ch R = 1 ,360     ,20.0321,20.0001,19.9921
XS GIS Cut Line= 3
      1135853.49      1696321.85      1135846.67      1696340.65
      1135839.85      1696359.45
#Sta/Elev= 18
       0174.2289 14.6972  174.05  15.002 174.064 17.6799173.7579 18.4279173.6549
 18.5949 173.593 18.8659173.5921 19.3009173.6001 19.7669173.6629 20.0001173.6689
 21.5719173.7089 21.8401173.7549  22.593173.8829 24.2289173.9369 24.3401173.9247
  29.786 173.936 35.7899174.1889 40.0001174.1639
#Mann= 3 , 0 , 0
       0     .02       0  15.002     .03       0 24.3401     .02       0
Bank Sta=15.002,24.3401
XS Rating Curve= 0 ,0
Exp/Cntr=0.3,0.1

Type RM Length L Ch R = 1 ,340     ,8.2141,7.5401,7.1009
XS GIS Cut Line= 3
      1135872.51      1696328.88      1135865.42      1696347.59
1135862.509342621696355.27775324
#Sta/Elev= 16
       0 175.096   10.91174.9729  16.123174.3889  16.518173.9759   17.96173.7781
 18.4111173.7159 18.9159 173.529 18.9589 173.529 20.0001173.5488 20.2741 173.554
 21.6801173.7451 21.8801  173.75 22.0181 173.754 25.1201   174.6  25.502 174.369
   27.93 174.199
#Mann= 3 , 0 , 0
       0     .02       0  16.123     .03       0 25.1201     .02       0
Bank Sta=16.123,25.1201
XS Rating Curve= 0 ,0
Exp/Cntr=0.3,0.1

Type RM Length L Ch R = 1 ,332.46  ,4.8189,6.06,7.007
XS GIS Cut Line= 3
      1135877.51      1696342.52      1135871.76      1696351.56
        1135861.      1696368.42
#Sta/Elev= 21
       0 175.207  3.7429175.0817  7.4261174.7586  8.7279174.2779   8.816174.0161
   8.984 173.512   9.034173.4861  9.0961 173.483  9.7929173.5351 10.7159173.5741
 11.1459 173.593 11.8909 173.633 12.2371173.8631 12.2749 173.879 12.2871 173.879
 16.3988173.8409  18.779173.8561 24.3779173.8119    26.2173.8799  28.326173.9061
 30.7159173.9061
#Mann= 3 , 0 , 0
       0     .02       0   8.816     .03       0 12.2871     .02       0
Bank Sta=8.816,12.2871
XS Rating Curve= 0 ,0
Exp/Cntr=0.3,0.1

Type RM Length L Ch R = 1 ,326.4   ,5.245,6.3999,7.1149
XS GIS Cut Line= 3
      1135878.04       1696342.7      1135877.27      1696353.95
      1135875.94      1696373.91
#Sta/Elev= 21
       0 175.224  2.3439174.9899  8.0781173.9689  8.1549 173.975   8.168173.9329
   8.197 173.918   8.937173.5339  10.052173.4861  10.088173.4879 10.1779173.4919
 11.2849 173.562 12.3161173.6269  13.132173.6821 13.1381173.6921 13.2929173.9609
  13.421  173.96 17.8869173.8939  20.488   173.7  20.577  173.71 20.7081173.8235
  31.285  173.91
#Mann= 3 , 0 , 0
       0     .02       0  8.0781     .03       0  13.421     .02       0
Bank Sta=8.0781,13.421
XS Rating Curve= 0 ,0
Exp/Cntr=0.3,0.1

Type RM Length L Ch R = 1 ,320     ,8.62,8.2601,8.029
XS GIS Cut Line= 3
      1135879.99      1696341.79      1135883.49       1696352.7
1135884.381027721696355.46756407
#Sta/Elev= 16
       0175.3801    .645 175.388  2.5789175.2499  4.7509 174.914  8.6371173.9801
  8.7472173.9259  9.0541 173.775   9.507173.5751  9.9051 173.526 10.3781173.5001
 11.4641173.5391  11.718173.5479  12.769 173.619  13.121174.2731 13.1689174.3608
 14.3689174.3678
#Mann= 3 , 0 , 0
       0     .02       0  4.7509     .03       0 13.1689     .02       0
Bank Sta=4.7509,13.1689
XS Rating Curve= 0 ,0
Exp/Cntr=0.3,0.1

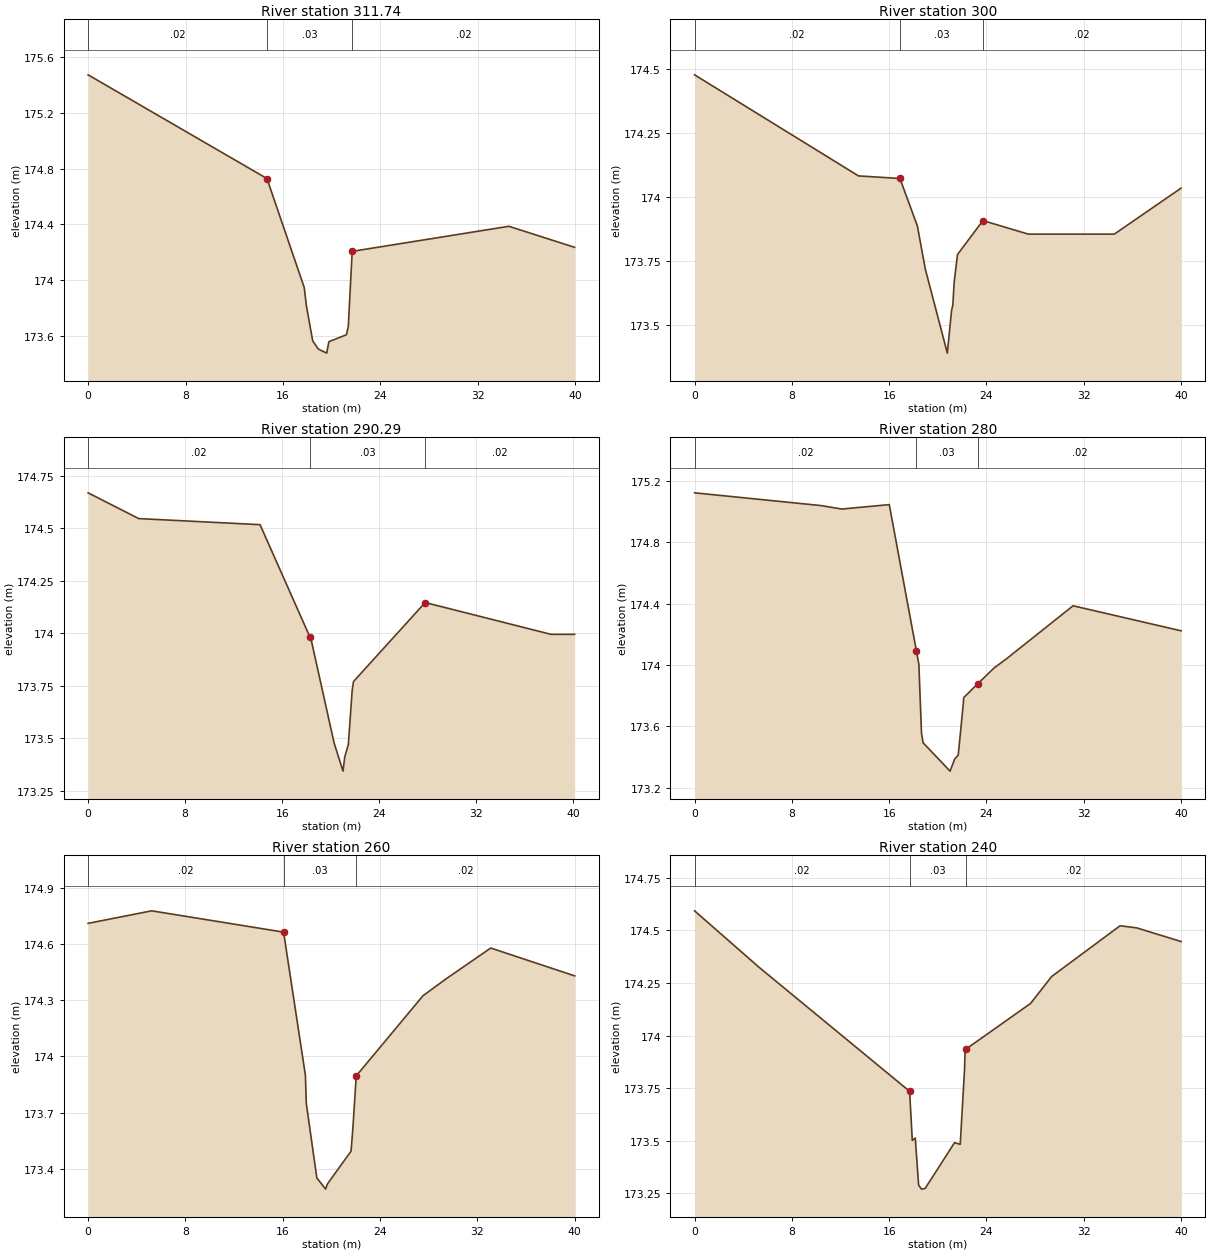
Type RM Length L Ch R = 1 ,311.74  ,12.3051,11.74,11.302
XS GIS Cut Line= 3
      1135887.99       1696331.8      1135891.57      1696351.08
      1135895.28      1696371.08
#Sta/Elev= 16
       0 175.474 14.6871 174.729 17.4599174.0201   17.75 173.946  17.928173.8149
  18.445173.5629 18.9119173.5041  19.595173.4751  19.613173.4839  19.773173.5571
  21.215173.6071 21.3689 173.668 21.4549 173.814 21.6871 174.206 34.5549174.3861
 39.9541 174.235
#Mann= 3 , 0 , 0
       0     .02       0 14.6871     .03       0 21.6871     .02       0
Bank Sta=14.6871,21.6871
XS Rating Curve= 0 ,0
Exp/Cntr=0.3,0.1

Type RM Length L Ch R = 1 ,300     ,9.7079,9.71,9.6859
XS GIS Cut Line= 3
      1135904.99      1696331.59       1135903.3      1696351.52
       1135901.6      1696371.45
#Sta/Elev= 17
       0174.4779 13.4761 174.082  16.885174.0719 18.3231173.8851 18.3599 173.875
 18.9701173.7171 20.0001  173.53  20.781173.3879 21.1281173.5549 21.2339 173.576
 21.3439173.6659    21.4173.6882  21.617173.7741  23.707 173.907 27.4411 173.854
 34.5101 173.854 40.0001174.0341
#Mann= 3 , 0 , 0
       0     .02       0  16.885     .03       0  23.707     .02       0
Bank Sta=16.885,23.707
XS Rating Curve= 0 ,0
Exp/Cntr=0.3,0.1

Type RM Length L Ch R = 1 ,290.29  ,10.4949,10.29,10.113
XS GIS Cut Line= 3
      1135914.66      1696332.41      1135912.97      1696352.34
      1135910.96      1696372.35
#Sta/Elev= 16
       0174.6699  4.1721174.5471  14.175174.5181 18.2901 173.982 18.3941173.9679
 20.0001173.5501 20.2921173.4751  21.016173.3431 21.1549173.4099  21.457173.4711
 21.6591173.6369   21.77173.7269 21.8788173.7701 27.7889174.1469 38.1732173.9951
 40.1098173.9951
#Mann= 3 , 0 , 0
       0     .02       0 18.2901     .03       0 27.7889     .02       0
Bank Sta=18.2901,27.7889
XS Rating Curve= 0 ,0
Exp/Cntr=0.3,0.1

Type RM Length L Ch R = 1 ,280     ,20.118,20.0001,19.8791
XS GIS Cut Line= 3
       1135927.1      1696334.17      1135923.15      1696353.77
      1135919.21      1696373.38
#Sta/Elev= 20
       0175.1219   10.38 175.039  12.107175.0162 16.0081175.0451 18.2401174.0911
  18.441174.0051 18.6559173.5559  18.794173.4931 20.0001173.3931  21.005 173.309
 21.3811 173.387  21.678173.4141 21.8801 173.576  22.087 173.743 22.1309173.7881
   23.27173.8771   24.64 173.982 25.5861174.0371 31.1201174.3861 40.0001174.2231
#Mann= 3 , 0 , 0
       0     .02       0 18.2401     .03       0   23.27     .02       0
Bank Sta=18.2401,23.27
XS Rating Curve= 0 ,0
Exp/Cntr=0.3,0.1

Type RM Length L Ch R = 1 ,260     ,19.7251,20.0001,20.2561
XS GIS Cut Line= 3
      1135947.68      1696339.66      1135942.47      1696358.97
      1135937.26      1696378.28
#Sta/Elev= 17
       0 174.712  5.2291 174.779 16.0721 174.665 17.8659173.8991 17.8799173.8689
 17.9369  173.75 18.8049173.3501 19.5291173.2901 19.6529173.3151 20.0001173.3471
 21.6179173.4931 21.7591173.6071  22.045 173.896 27.5359174.3249  29.472174.4169
  33.104  174.58 40.0001 174.431
#Mann= 3 , 0 , 0
       0     .02       0 16.0721     .03       0  22.045     .02       0
Bank Sta=16.0721,22.045
XS Rating Curve= 0 ,0
Exp/Cntr=0.3,0.1

Type RM Length L Ch R = 1 ,240     ,20.0961,20.0001,19.9031
XS GIS Cut Line= 3
      1135964.81       1696343.5      1135961.97       1696363.3
      1135959.12      1696383.09
#Sta/Elev= 19
       0174.5931  5.2721174.3261  17.679173.7351    17.9173.5019  18.145173.5129
 18.4209173.2889 18.6599  173.27 18.9519 173.273 20.0001173.3669 21.3711173.4909
  21.842 173.483 22.1989173.8421 22.2379 173.932 22.3199173.9359 27.6289 174.153
  29.362 174.281  34.984174.5221 36.3541 174.512 40.0001174.4471
#Mann= 3 , 0 , 0
       0     .02       0  17.679     .03       0 22.3199     .02       0
Bank Sta=17.679,22.3199
XS Rating Curve= 0 ,0
Exp/Cntr=0.3,0.1

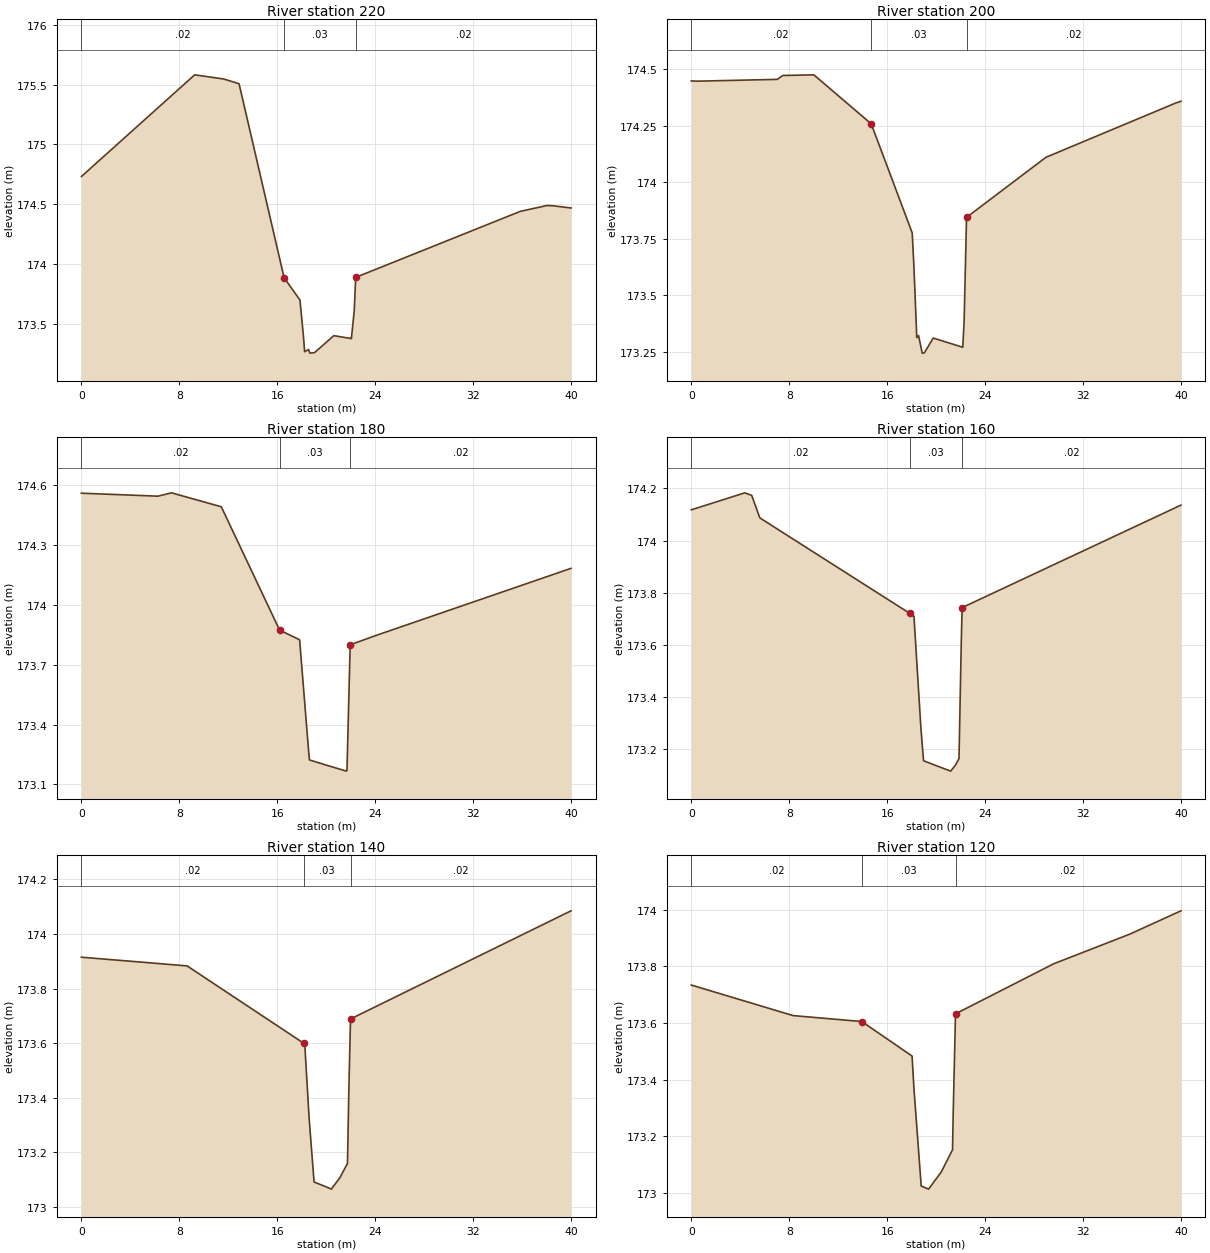
Type RM Length L Ch R = 1 ,220     ,20.0369,20.0001,19.9699
XS GIS Cut Line= 3
      1135985.32      1696347.32      1135981.62      1696366.98
      1135977.93      1696386.63
#Sta/Elev= 22
       0174.7309  9.2549175.5809 11.6321175.5459 12.8808175.5063 16.5601173.8851
 17.6799173.7241  17.854173.6991  18.145 173.391 18.2371173.2669  18.555173.2849
 18.6699 173.255 19.0439 173.259 20.0001173.3449 20.6191 173.401 22.0401 173.377
 22.0569 173.376 22.2919173.6129 22.4089173.8881  35.864174.4401 38.0409174.4888
 38.4719 174.487 40.0001174.4681
#Mann= 3 , 0 , 0
       0     .02       0 16.5601     .03       0 22.4089     .02       0
Bank Sta=16.5601,22.4089
XS Rating Curve= 0 ,0
Exp/Cntr=0.3,0.1

Type RM Length L Ch R = 1 ,200     ,20.2601,20.0001,19.7739
XS GIS Cut Line= 3
      1136005.28      1696351.16      1136001.26      1696370.75
      1135997.24      1696390.35
#Sta/Elev= 22
       0 174.448    .555174.4471   7.022 174.455  7.4639174.4721 10.0121174.4751
 14.6999174.2581    17.8 173.811 18.0469 173.775 18.1819 173.633 18.4209 173.312
 18.5681173.3209 18.8629173.2431  19.036 173.244 19.7669173.3099 20.0001173.3059
 21.8401173.2748  22.176173.2691 22.2879 173.383 22.4839173.8439 28.9718  174.11
 39.5591174.3499 40.0001174.3581
#Mann= 3 , 0 , 0
       0     .02       0 14.6999     .03       0 22.4839     .02       0
Bank Sta=14.6999,22.4839
XS Rating Curve= 0 ,0
Exp/Cntr=0.3,0.1

Type RM Length L Ch R = 1 ,180     ,19.994,20.0001,20.0141
XS GIS Cut Line= 3
      1136026.99      1696356.31      1136020.72       1696375.3
      1136014.46       1696394.3
#Sta/Elev= 18
       0174.5581  6.2481174.5431  7.3609174.5599 11.4291174.4901 16.1919173.8728
   17.64173.8299 17.8271173.8241 18.6029 173.238   18.63 173.223 20.0001173.1971
 21.6509173.1669 21.6749173.1691  21.696173.1709 21.8801 173.611  21.955173.7909
 21.9599173.7991 24.0249173.8451 40.0001174.1819
#Mann= 3 , 0 , 0
       0     .02       0 16.1919     .03       0 21.9599     .02       0
Bank Sta=16.1919,21.9599
XS Rating Curve= 0 ,0
Exp/Cntr=0.3,0.1

Type RM Length L Ch R = 1 ,160     ,20.0601,20.0001,19.9531
XS GIS Cut Line= 3
      1136045.91      1696362.46      1136039.74      1696381.49
      1136033.58      1696400.51
#Sta/Elev= 16
       0174.1179  4.3739174.1831  4.9381174.1731   5.597174.0871 17.8399173.7211
 18.1889173.7101  18.758173.2809  18.972 173.156 20.0001173.1371  21.187 173.116
   21.55173.1371    21.6 173.141 21.8691173.1639 22.0599173.6199  22.126 173.743
 40.0001174.1359
#Mann= 3 , 0 , 0
       0     .02       0 17.8399     .03       0  22.126     .02       0
Bank Sta=17.8399,22.126
XS Rating Curve= 0 ,0
Exp/Cntr=0.3,0.1

Type RM Length L Ch R = 1 ,140     ,20.001,20.0001,20.0001
XS GIS Cut Line= 3
      1136065.39      1696369.13      1136058.66      1696387.96
      1136051.94       1696406.8
#Sta/Elev= 14
       0173.9149   8.638173.8829   18.16173.5992  18.245 173.597 18.6059 173.323
 19.0089173.0901 20.0001173.0722 20.4179173.0639 21.1199 173.106 21.5201173.1401
 21.7371173.1581  21.859173.4489 21.9871173.6882 40.0001 174.085
#Mann= 3 , 0 , 0
       0     .02       0   18.16     .03       0 21.9871     .02       0
Bank Sta=18.16,21.9871
XS Rating Curve= 0 ,0
Exp/Cntr=0.3,0.1

Type RM Length L Ch R = 1 ,120     ,19.6249,20.0001,20.3451
XS GIS Cut Line= 3
      1136084.22      1696375.85       1136077.5      1696394.69
      1136070.78      1696413.52
#Sta/Elev= 16
       0173.7339   8.307 173.626 13.9321173.6049 18.0371 173.483 18.1911 173.366
 18.2801173.3151 18.7821 173.024  19.385 173.013 20.0001 173.049 20.4259 173.074
 21.3409 173.152 21.3939173.2779 21.5841173.6321 29.6119173.8091 35.8411 173.914
 40.0001 173.996
#Mann= 3 , 0 , 0
       0     .02       0 13.9321     .03       0 21.5841     .02       0
Bank Sta=13.9321,21.5841
XS Rating Curve= 0 ,0
Exp/Cntr=0.3,0.1

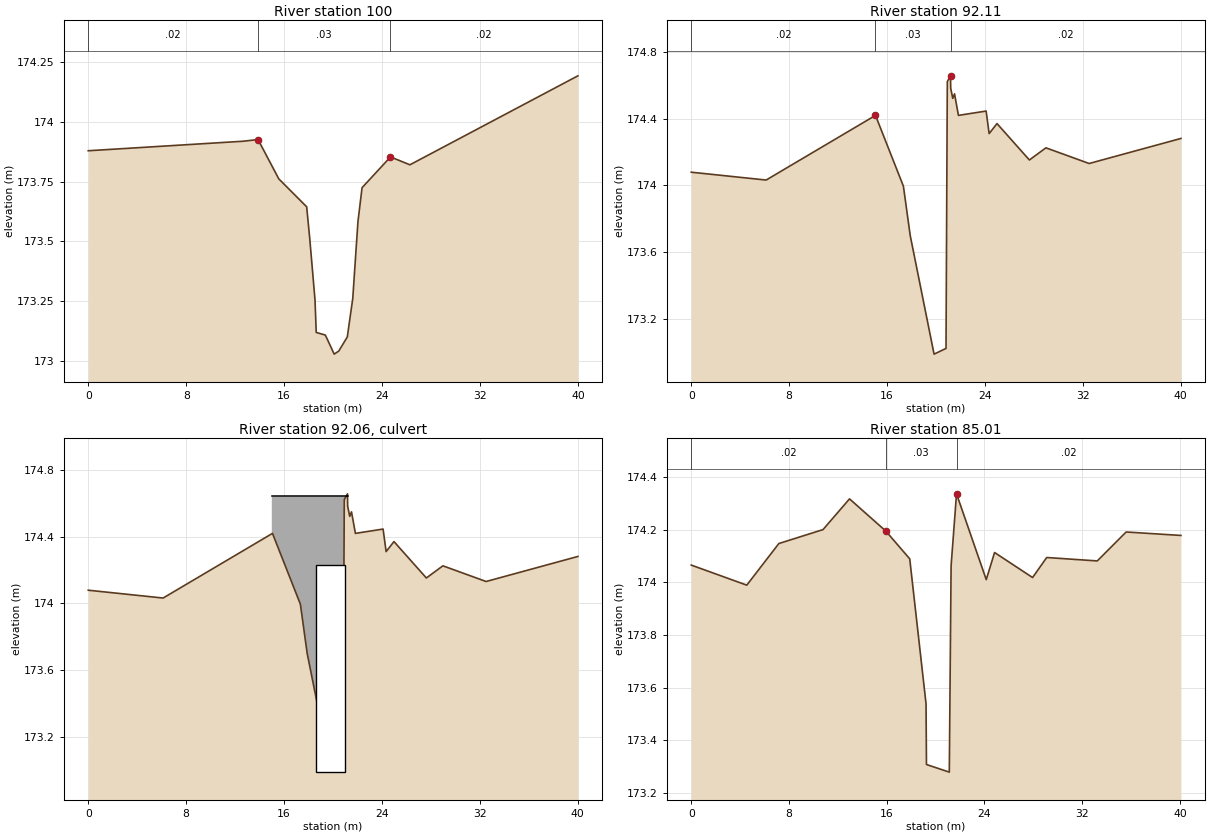
Type RM Length L Ch R = 1 ,100     ,8.4609,7.8901,7.916
XS GIS Cut Line= 3
      1136099.22      1696380.43      1136096.65      1696400.27
      1136094.08       1696420.1
#Sta/Elev= 20
       0173.8799 12.6541173.9198 13.8699173.9268 15.5661173.7619 17.8421173.6449
 18.0981173.5089  18.523173.2541 18.6239173.1179 19.3691173.1069 20.0001173.0371
 20.0881 173.027 20.4631173.0398  21.162 173.099 21.6091173.2611 21.7999173.4071
 22.0319 173.583 22.3671 173.725   24.69 173.854  26.278 173.821 40.0001174.1941
#Mann= 3 , 0 , 0
       0     .02       0 13.8699     .03       0   24.69     .02       0
Bank Sta=13.8699,24.69
XS Rating Curve= 0 ,0
Exp/Cntr=0.3,0.1

Type RM Length L Ch R = 1 ,92.11   ,7.239,7.1,7.2369
XS GIS Cut Line= 3
       1136108.7      1696382.06       1136104.4      1696401.73
      1136100.15      1696421.16
#Sta/Elev= 20
       0174.0789  6.1179 174.032 15.0559174.4191 17.3379173.9951 17.8939   173.7
  19.844172.9899   20.82 173.024  20.926174.6211 21.1879174.6559 21.2031174.5821
 21.3701174.5209 21.5161 174.548 21.8359174.4191 24.0981 174.445 24.3459  174.31
 24.9881  174.37  27.635174.1521 28.9871174.2249 32.5191 174.131 40.0221 174.281
#Mann= 3 , 0 , 0
       0     .02       0 15.0559     .03       0 21.1879     .02       0
Bank Sta=15.0559,21.1879
XS Rating Curve= 0 ,0
Exp/Cntr=0.3,0.1

Type RM Length L Ch R = 2 ,92.06   ,,,
BEGIN DESCRIPTION:
Carrera 1
END DESCRIPTION:
Bridge Culvert--1,0,-1,-1, 0
Deck Dist Width WeirC Skew NumUp NumDn MinLoCord MaxHiCord MaxSubmerge Is_Ogee
0.05,7.05,1.24,0, 2, 2, , , 0.98, 0, 0,0,,
      15    21.2
  174.64  174.64
  172.99  172.99
    12.8    21.5
  174.62  174.62
   173.3   173.3
BR Coef=-1 , 0 , 0 ,, 0 ,,,0.8,-1,,0,
WSPro=,,,, 1 ,,,, 0 ,,,, 0 ,,,,-1 ,-1 ,-1 , 0 , 0 , 0 , 0 , 0
Culvert=2,1.24,2.3,7.05,0.015,0.2,0.1,8,1,172.99,19.8,173.3,20.2,Culvert #1  , 0 ,0.05
    19.8    20.2
BC Culvert Barrel=1,Barrel#1,0
Culvert Bottom n=0.015
BC Design=,, 0 ,, 0 ,,,,,,
BC Use User HTab Curves=0
BC User HTab FreeFlow(D)= 0

Type RM Length L Ch R = 1 ,85.01   ,5.7601,5.01,5.184
XS GIS Cut Line= 3
      1136116.02      1696383.37      1136111.36      1696403.16
       1136106.8      1696422.38
#Sta/Elev= 19
       0174.0661   4.543173.9899   7.168174.1481  10.785174.2011 12.9549174.3179
 15.9191174.1959 17.8851174.0899 19.2201173.5391 19.2551173.3081 21.1251173.2791
  21.272 174.063  21.717174.3371 24.1511174.0109 24.8321 174.114  27.945174.0188
 29.0999 174.095 33.2409 174.082  35.604 174.192  40.091174.1789
#Mann= 3 , 0 , 0
       0     .02       0 15.9191     .03       0  21.717     .02       0
Bank Sta=15.9191,21.717
XS Rating Curve= 0 ,0
Exp/Cntr=0.3,0.1