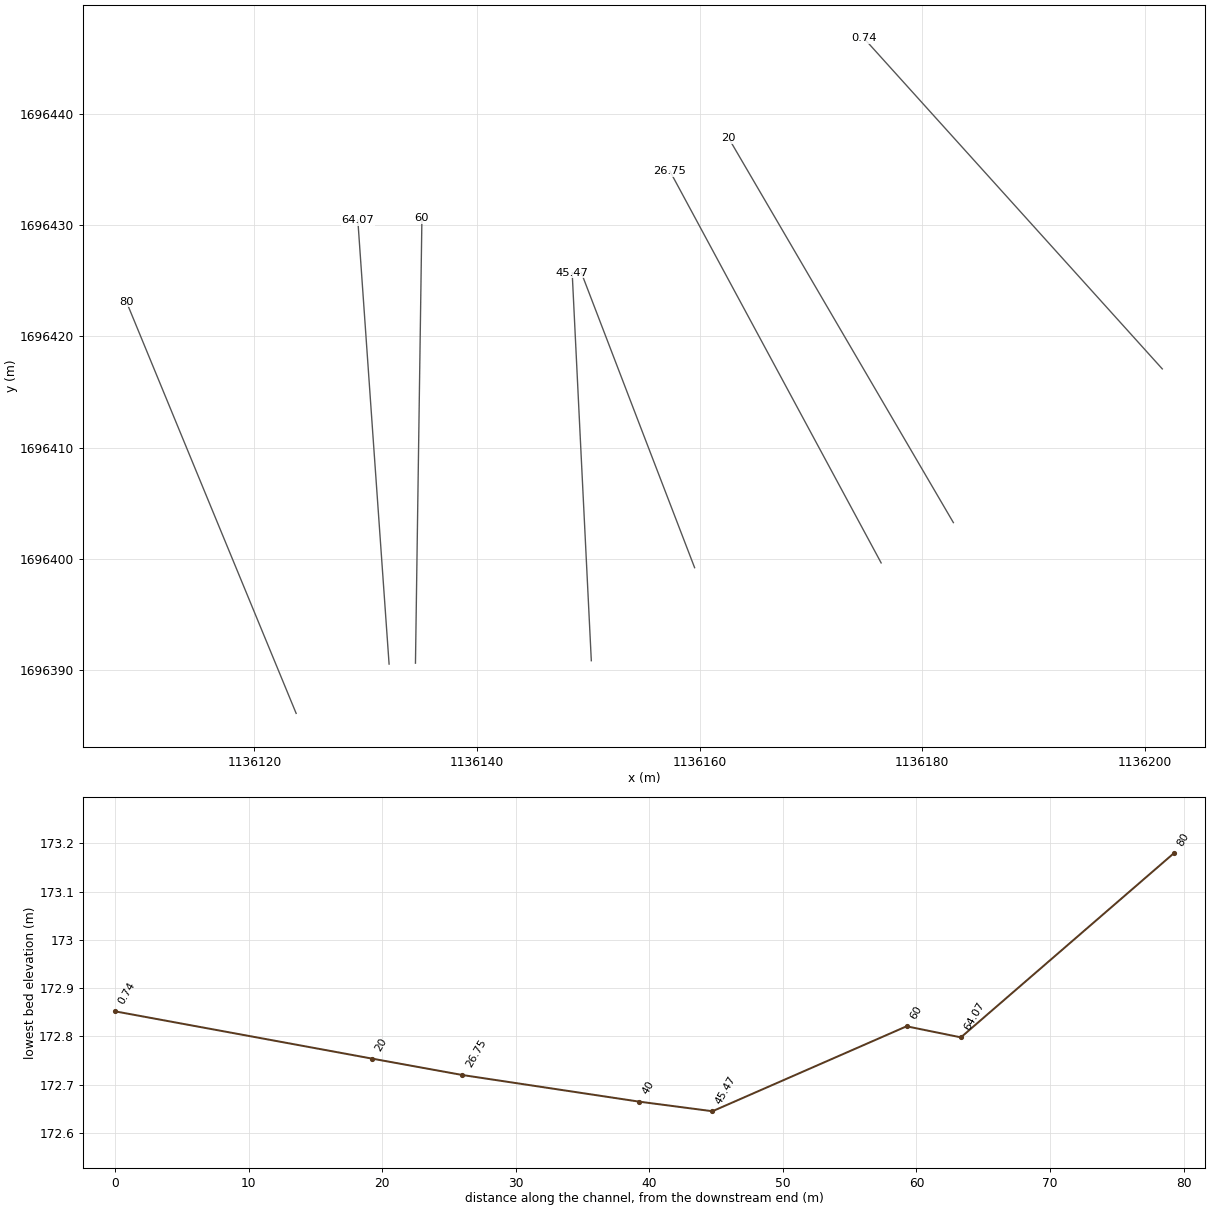
HEC-RAS study AcequiaDiseño.prj: Acequia Diseño

--- AcequiaDiseño.g01 (geometry) --- (continued)

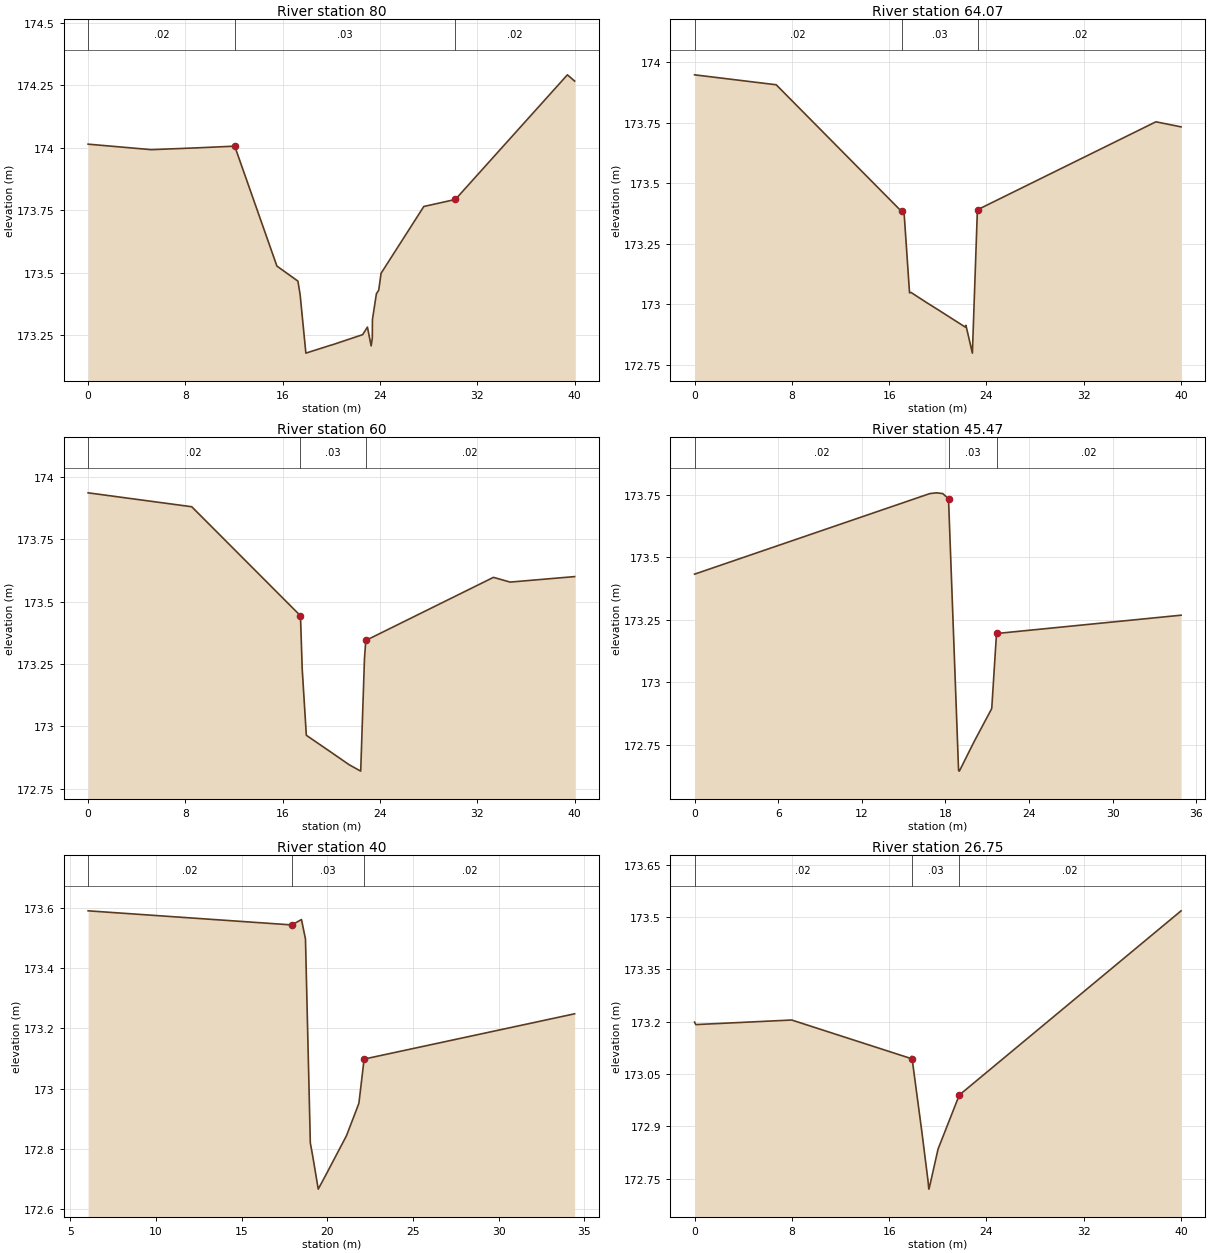
Type RM Length L Ch R = 1 ,80      ,14.9389,15.9301,17.6269
XS GIS Cut Line= 3
      1136123.76      1696386.12      1136116.13      1696404.61
      1136108.51       1696423.1
#Sta/Elev= 23
       0 174.014  5.1971 173.992    8.98173.9993 12.0539 174.006 15.5229173.5269
 17.2471173.4669   17.32173.4461 17.4309173.4129  17.904173.1791 19.9681173.2111
 20.0001173.2111 22.5701173.2529 22.9661173.2831 23.2709173.2081  23.366173.2389
  23.376173.3129 23.7009 173.416 23.8951173.4309 24.0859 173.498 27.6021 173.765
 30.1929 173.793 39.4061 174.291 40.0001174.2661
#Mann= 3 , 0 , 0
       0     .02       0 12.0539     .03       0 30.1929     .02       0
Bank Sta=12.0539,30.1929
XS Rating Curve= 0 ,0
Exp/Cntr=0.3,0.1

Type RM Length L Ch R = 1 ,64.07   ,3.863,4.07,4.351
XS GIS Cut Line= 3
      1136132.11      1696390.55       1136130.7       1696410.5
       1136129.3      1696430.45
#Sta/Elev= 19
       0173.9481  6.7129 173.907  17.013173.3839 17.1039173.3891  17.227 173.373
  17.237 173.369   17.28173.3379 17.6741173.0471  17.793 173.049  19.043173.0081
 20.0001 172.978  22.247 172.906 22.3101 172.913 22.8411172.7981 23.2501 173.387
  23.255 173.391   23.28 173.391 37.9321 173.754 40.0001 173.733
#Mann= 3 , 0 , 0
       0     .02       0  17.013     .03       0   23.28     .02       0
Bank Sta=17.013,23.28
XS Rating Curve= 0 ,0
Exp/Cntr=0.3,0.1

Type RM Length L Ch R = 1 ,60      ,14.6731,14.5301,14.449
XS GIS Cut Line= 3
      1136134.48      1696390.63      1136134.77      1696410.63
      1136135.06      1696430.62
#Sta/Elev= 14
       0173.9369   8.521173.8811 17.4599 173.444 17.5601 173.295 17.6019173.2319
 17.9411172.9648 20.0001 172.896 21.4549172.8469 22.4119 172.821 22.7219173.2721
 22.8301173.3449  33.325173.5979 34.7021 173.579 40.0001 173.601
#Mann= 3 , 0 , 0
       0     .02       0 17.4599     .03       0 22.8301     .02       0
Bank Sta=17.4599,22.8301
XS Rating Curve= 0 ,0
Exp/Cntr=0.3,0.1

Type RM Length L Ch R = 1 ,45.47   ,6.06,5.4699,4.9289
XS GIS Cut Line= 3
      1136150.28      1696390.85      1136149.29      1696410.83
      1136148.56      1696425.71
#Sta/Elev= 16
       0173.4321  16.878 173.754  17.359 173.757 17.8049 173.754 18.2179 173.733
 18.9369172.6509 18.9421 172.647 18.9939172.6451 20.0001 172.757 20.0921 172.767
 21.2881 172.892 21.3202172.8969 21.6359 173.174  21.667 173.195 21.6819 173.195
  34.902173.2681
#Mann= 3 , 0 , 0
       0     .02       0 18.2179     .03       0  21.667     .02       0
Bank Sta=18.2179,21.667
XS Rating Curve= 0 ,0
Exp/Cntr=0.3,0.1

Type RM Length L Ch R = 1 ,40      ,13.549,13.25,13.0241
XS GIS Cut Line= 3
1136159.560568811696399.21112539      1136154.55      1696412.24
      1136149.38      1696425.72
#Sta/Elev= 13
  6.0439173.5919 17.9411173.5449  18.495173.5629  18.729 173.498 19.0119172.8189
 19.1579172.7731  19.474172.6649 20.0001 172.721  21.122172.8429 21.6951 172.928
 21.8472172.9511  22.151173.0981  34.436173.2489
#Mann= 3 , 0 , 0
  6.0439     .02       0 17.9411     .03       0  22.151     .02       0
Bank Sta=17.9411,22.151
XS Rating Curve= 0 ,0
Exp/Cntr=0.3,0.1

Type RM Length L Ch R = 1 ,26.75   ,6.83,6.7501,6.6779
XS GIS Cut Line= 3
      1136176.32      1696399.64      1136166.82      1696417.26
      1136157.34      1696434.84
#Sta/Elev= 13
       0173.1989   .0981173.1919  7.9861 173.205 17.8399173.0941  17.857173.0929
 17.8579173.1011 18.6848 172.885  19.207172.7399 19.2579172.7201 19.3121172.7259
  20.019 172.835 21.7649172.9899 40.0001173.5181
#Mann= 3 , 0 , 0
       0     .02       0 17.8399     .03       0 21.7649     .02       0
Bank Sta=17.8399,21.7649
XS Rating Curve= 0 ,0
Exp/Cntr=0.3,0.1

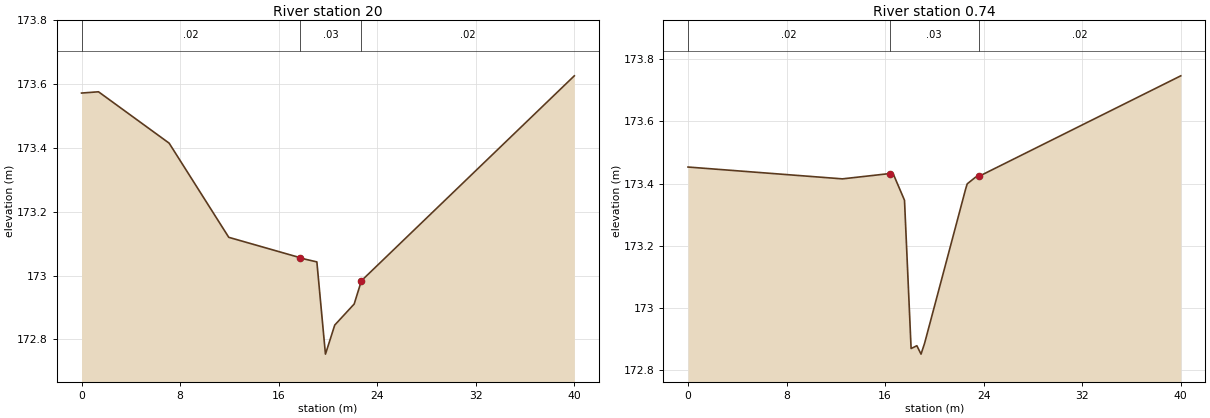
Type RM Length L Ch R = 1 ,20      ,19.7199,19.26,18.9131
XS GIS Cut Line= 3
      1136182.81      1696403.26      1136172.71      1696420.53
      1136162.62       1696437.8
#Sta/Elev= 14
       0 173.572   1.376 173.576    7.11 173.415   11.95  173.12   17.76 173.056
  18.199 173.051  19.102 173.043  19.798 172.754      20 172.778  20.552 172.845
  22.131 172.911  22.718 172.984   22.72 172.984      40 173.626
#Mann= 3 , 0 , 0
       0     .02       0   17.76     .03       0  22.718     .02       0
Bank Sta=17.76,22.718
XS Rating Curve= 0 ,0
Exp/Cntr=0.3,0.1

Type RM Length L Ch R = 1 ,0.74    ,,,
XS GIS Cut Line= 3
      1136201.58      1696417.07      1136188.18      1696431.92
      1136174.78      1696446.77
#Sta/Elev= 18
       0 173.453  12.533 173.415  16.363 173.432  16.636 173.433   17.48 173.355
  17.574 173.346  18.109  172.87  18.577 172.879  18.915 172.852  19.198 172.886
      20 173.005   22.52  173.38  22.578 173.388  22.666 173.399  23.327  173.42
  23.447 173.422  23.614 173.423      40 173.746
#Mann= 3 , 0 , 0
       0     .02       0  16.363     .03       0  23.614     .02       0
Bank Sta=16.363,23.614
XS Rating Curve= 0 ,0
Exp/Cntr=0.3,0.1
LCMann Table=0

Chan Stop Cuts=-1
Use User Specified Reach Order=0
Composite Channel Slope=5