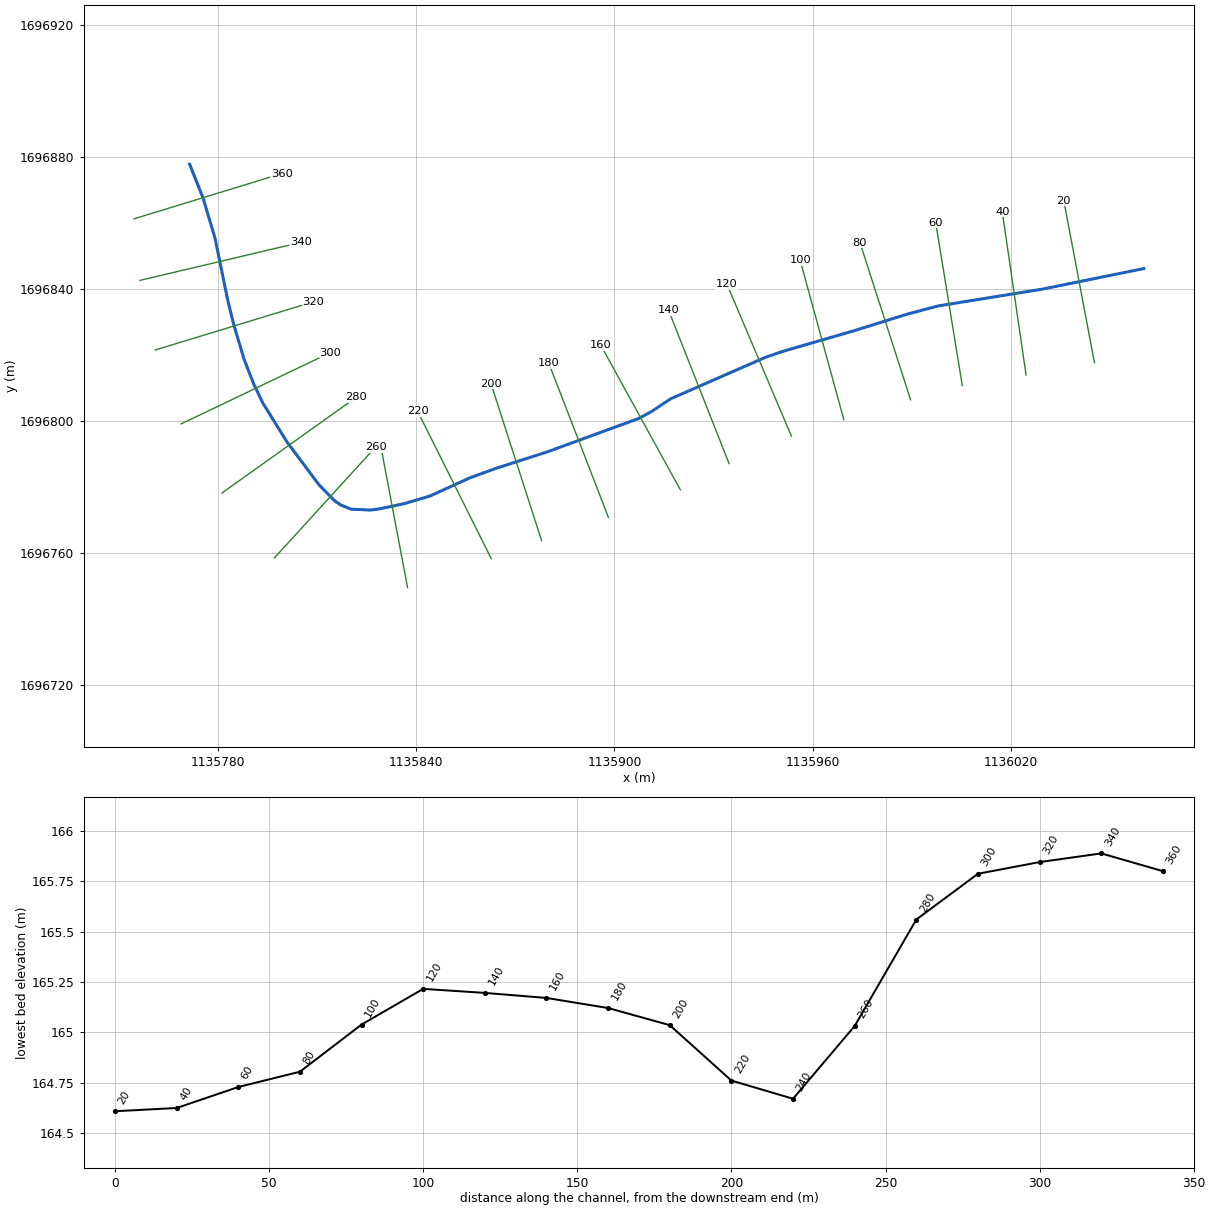
--- Rancheria.prj (project) ---

Proj Title=Rancheria
Current Plan=p01
Default Exp/Contr=0.3,0.1
SI Units
Geom File=g01
Flow File=f01
Flow File=f02
Plan File=p01
Y Axis Title=Elevation
X Axis Title(PF)=Main Channel Distance
X Axis Title(XS)=Station
BEGIN DESCRIPTION:
END DESCRIPTION:
DSS Export Rating Curves= 0
DSS Export Rating Curve Sorted= 0
DSS Export Volume Flow Curves= 0
DXF OffsetX= 0
DXF OffsetY= 0
DXF ScaleX= 1
DXF ScaleY= 10

--- Rancheria.p01 (plan) ---

Plan Title=Plan 01
Program Version=5.06
Short Identifier=Plan 02
Geom File=g01
Flow File=f01
Subcritical Flow
K Sum by GR= 0
Std Step Tol= 0.003
Critical Tol= 0.003
Num of Std Step Trials= 20
Max Error Tol= 0.1
Flow Tol Ratio= 0.001
Split Flow NTrial= 30
Split Flow Tol= 0.006
Split Flow Ratio= 0.02
Log Output Level= 0
Friction Slope Method= 1
Unsteady Friction Slope Method= 2
Unsteady Bridges Friction Slope Method= 1
Parabolic Critical Depth
Global Vel Dist= 0 , 0 , 0
Global Log Level= 0
CheckData=True
Encroach Param=-1 ,0,0, 0
Computation Interval=1MIN
Output Interval=1HOUR
Instantaneous Interval=1HOUR
Mapping Interval=1HOUR
Computation Time Step Use Courant=        0
Computation Time Step Use Time Series=    0
Computation Time Step Count To Double=0
Computation Time Step Max Doubling=0
Computation Time Step Max Halving=0
Computation Time Step Residence Courant=0
Run HTab= 0
Run UNet= 0
Run Sediment= 0
Run PostProcess= 0
Run WQNet= 0
Run RASMapper= 0
UNET Theta= 1
UNET Theta Warmup= 1
UNET ZTol= 0.006
UNET ZSATol= 0.006
UNET MxIter= 20
UNET Max Iter WO Improvement= 0
UNET MaxInSteps= 0
UNET DtIC= 0
UNET DtMin= 0
UNET MaxCRTS= 20
UNET WFStab= 2
UNET SFStab= 1
UNET WFX= 1
UNET SFX= 1
UNET 1D Methodology=Finite Difference
UNET DSS MLevel= 4
UNET Pardiso=0
UNET DZMax Abort= 30
UNET Use Existing IB Tables=-1
UNET Froude Reduction=False
UNET Froude Limit= 0.8
UNET Froude Power= 4
UNET D1 Cores= 0
UNET D2 Coriolis=0
UNET D2 Cores= 0
UNET D2 Theta= 1
UNET D2 Theta Warmup= 1
UNET D2 Z Tol= 0.003
UNET D2 Volume Tol= 0.003
UNET D2 Max Iterations= 20
UNET D2 Equation= 0
UNET D2 RampUpFraction=0.1
UNET D2 TimeSlices= 1
UNET D2 BCVolumeCheck=0
UNET D1D2 MaxIter= 0
UNET D1D2 ZTol=0.003
UNET D1D2 QTol=0.1
UNET D1D2 MinQTol=0.03
Write IC File= 0
Write IC File at Fixed DateTime=0
Write IC File at Sim End=0
Echo Input=False
Echo Parameters=False
Echo Output=False
Write Detailed= 0
HDF Write Warmup=0
HDF Write Time Slices=0
HDF Flush=0
HDF Face Node Velocities=0
HDF Compression= 1
HDF Chunk Size= 1
HDF Spatial Parts= 1
HDF Use Max Rows=0
HDF Fixed Rows= 1
Calibration Method= 0
Calibration Iterations= 20
Calibration Max Change=0.05
Calibration Tolerance=0.2
Calibration Maximum=1.5
Calibration Minimum=0.5
Calibration Optimization Method= 1
WQ AD Non Conservative
WQ ULTIMATE=-1
WQ Max Comp Step=1HOUR
WQ Output Interval=15MIN
WQ Output Selected Increments= 0
WQ Output face flow=0
WQ Output face velocity=0
WQ Output face area=0
WQ Output face dispersion=0
WQ Output cell volume=0
WQ Output cell surface area=0
WQ Output cell continuity=0
WQ Output cumulative cell continuity=0
WQ Output face conc=0
WQ Output face dconc_dx=0
WQ Output face courant=0
WQ Output face peclet=0
WQ Output face adv mass=0
WQ Output face disp mass=0
WQ Output cell mass=0
WQ Output cell source sink temp=0
WQ Output nsm pathways=0
WQ Output nsm derived pathways=0
WQ Output MaxMinRange=-1
WQ Daily Max Min Mean=-1
WQ Daily Range=0
WQ Daily Time=0
WQ Create Restart=0
WQ Fixed Restart=0
WQ System Summary=0
WQ Write To DSS=0
WQ Use Fixed Temperature=0
Sorting and Armoring Iterations= 10
XS Update Threshold= 0.02
Bed Roughness Predictor= 0
Hydraulics Update Threshold= 0.02
Energy Slope Method= 1
Volume Change Method= 1
Sediment Retention Method= 0
XS Weighting Method= 0
Number of US Weighted Cross Sections= 1
Number of DS Weighted Cross Sections= 1
Upstream XS Weight=0
Main XS Weight=1
Downstream XS Weight=0
Number of DS XS's Weighted with US Boundary= 1
Upstream Boundary Weight= 1
Weight of XSs Associated with US Boundary= 0
Number of US XS's Weighted with DS Boundary= 1
Downstream Boundary Weight= 0.5
Weight of XSs Associated with DS Boundary= 0.5
Percentile Method= 0
Sediment Output Level= 3
Mass or Volume Output= 0
Output Increment Type= 1
Profile and TS Output Increment= 1
XS Output Flag= 0
XS Output Increment= 10
Write Gradation File= 0
Read Gradation Hotstart= 0
Write HDF5 File= 1
Write Binary Output= 1
Write DSS Sediment File= 0
SV Curve= 0
Specific Gage Flag= 0

--- Rancheria.f01 (steady flow) ---

Flow Title=Flow 01
Program Version=5.06
Number of Profiles= 4
Profile Names=PF 1,PF 2,PF 3,PF 4
River Rch & RM=Rancheria,rio             ,360
   26.17   56.51   86.49   99.16
Boundary for River Rch & Prof#=Rancheria,rio             , 1
Up Type= 0
Dn Type= 3
Dn Slope=0.006
Boundary for River Rch & Prof#=Rancheria,rio             , 2
Up Type= 0
Dn Type= 3
Dn Slope=0.006
Boundary for River Rch & Prof#=Rancheria,rio             , 3
Up Type= 0
Dn Type= 3
Dn Slope=0.006
Boundary for River Rch & Prof#=Rancheria,rio             , 4
Up Type= 0
Dn Type= 3
Dn Slope=0.006
DSS Import GetInterval= 0
DSS Import GetPeak= 0
DSS Import FillOption= 0

--- Rancheria.f02 (steady flow) ---

Flow Title=Flow 02
Program Version=5.06
Number of Profiles= 1
Profile Names=PF 1
DSS Import GetInterval= 0
DSS Import GetPeak= 0
DSS Import FillOption= 0

--- Rancheria.g01 (geometry) ---

Geom Title=Rancheria-geo
Program Version=5.06

River Reach=Rancheria       ,rio
Reach XY= 30
      1136060.34      1696846.11      1136029.61      1696839.88
      1135997.94      1696834.77      1135988.52      1696832.26
      1135972.33      1696827.21       1135950.8      1696820.98
      1135945.55      1696819.15        1135917.      1696806.65
       1135911.2       1696802.8       1135907.5      1696800.77
      1135879.73      1696790.62      1135864.19      1696785.63
      1135856.17      1696782.71      1135844.15      1696777.23
      1135836.47      1696774.95      1135828.84      1696773.34
      1135826.12      1696772.98      1135820.26      1696773.24
      1135817.18      1696774.49      1135815.24       1696775.8
      1135810.54      1696780.62      1135800.86      1696793.57
      1135793.54      1696805.36      1135790.74       1696811.2
      1135787.85      1696818.63      1135784.65      1696829.37
      1135782.81      1696836.96      1135779.04      1696855.35
      1135775.38      1696867.61      1135771.34      1696877.73

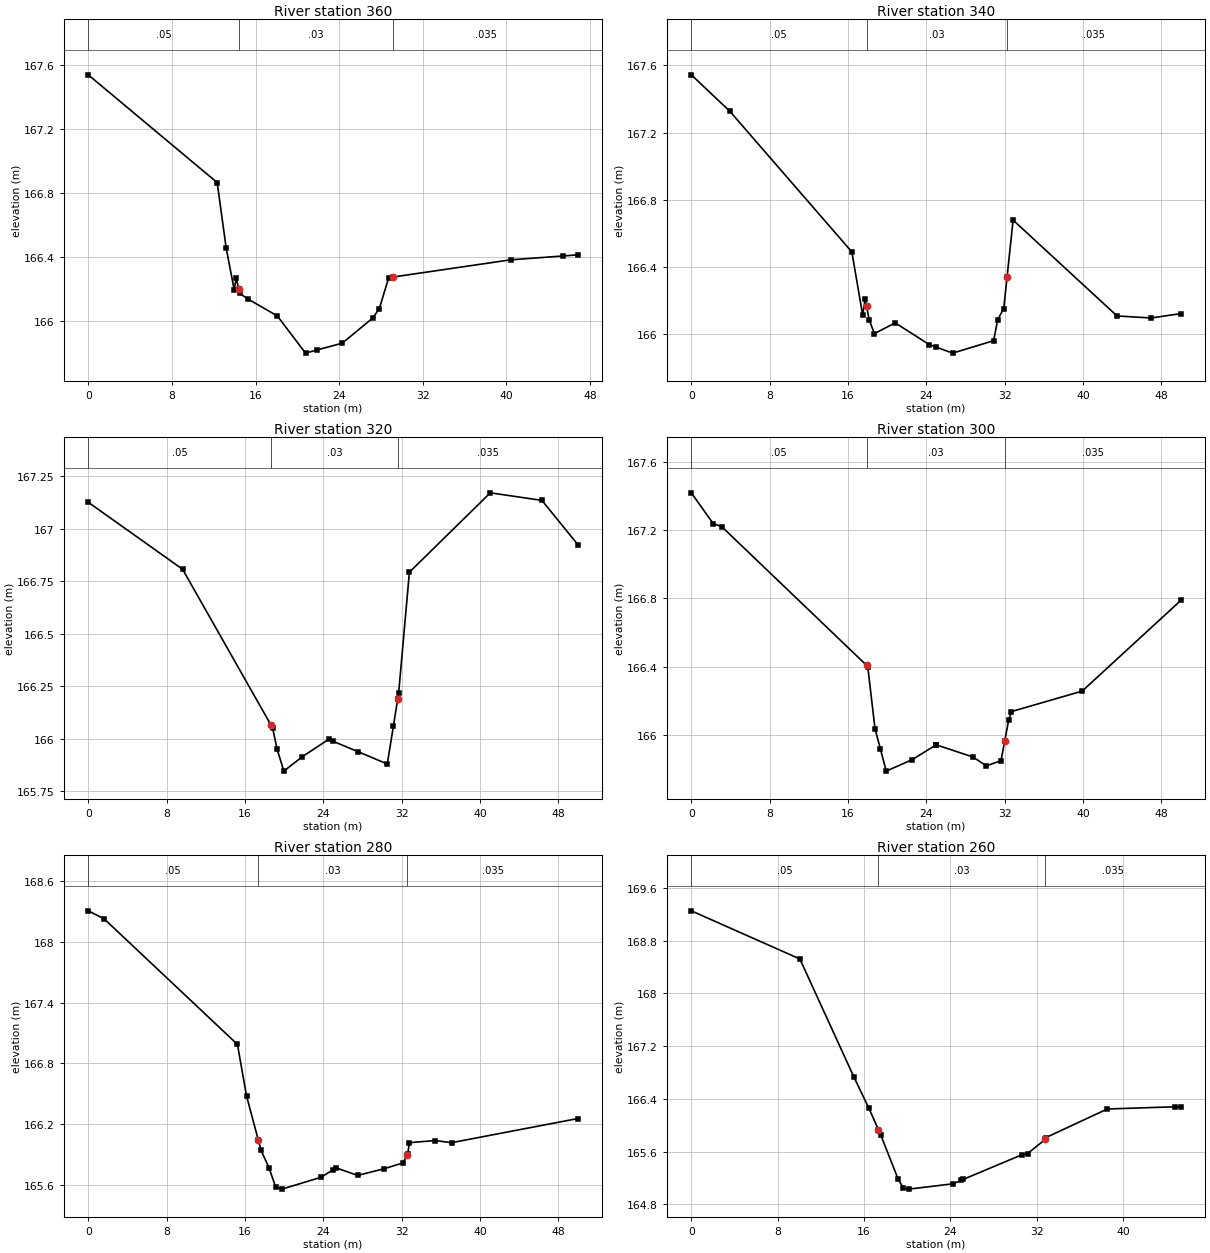
Type RM Length L Ch R = 1 ,360     ,19.518,20,20.511
XS GIS Cut Line= 3
 1135754.51872471696861.167301781135775.390791431696867.56468029
1135799.293234121696874.89088212
#Sta/Elev= 19
       0 167.536  12.329 166.864  13.191 166.455  13.955 166.196  14.154 166.269
  14.377 166.201  14.467 166.173  15.315 166.136  18.082 166.032  20.781   165.8
   21.83 165.819  24.291 165.862  27.227  166.02  27.837 166.078  28.737 166.271
  29.175 166.275  40.399 166.382  45.393 166.406   46.83 166.413
#Mann= 3 , 0 , 0
       0     .05       0  14.377     .03       0  29.175    .035       0
Bank Sta=14.377,29.175
XS Rating Curve= 0 ,0
Exp/Cntr=0.3,0.1

Type RM Length L Ch R = 1 ,340     ,20.397,20,19.652
XS GIS Cut Line= 3
1135756.307379041696842.528706381135780.637594911696848.27680136
1135804.967810771696854.02489633
#Sta/Elev= 20
       0 167.543   3.924 167.327  16.394  166.49  17.502 166.114  17.757 166.209
    17.9 166.166  18.169 166.085  18.698 166.004  20.823 166.068  24.292 165.939
      25 165.924  26.685 165.888  30.871 165.962   31.29 166.087  31.905 166.153
   32.25 166.343  32.861 166.679  43.476 166.109  46.948 166.097      50 166.123
#Mann= 3 , 0 , 0
       0     .05       0    17.9     .03       0   32.25    .035       0
Bank Sta=17.9,32.25
XS Rating Curve= 0 ,0
Exp/Cntr=0.3,0.1

Type RM Length L Ch R = 1 ,320     ,21.028,20,19.017
XS GIS Cut Line= 3
1135760.92631262 1696821.44999961135784.841628191696828.73406998
1135808.756943751696836.01814037
#Sta/Elev= 18
       0 167.125   9.633 166.806   18.65 166.065  18.823 166.051  19.267 165.952
  19.972 165.845   21.84 165.913  24.533 165.996      25 165.987   27.58 165.937
  30.534 165.879  31.157 166.059    31.6 166.189  31.696 166.217  32.792 166.792
  41.054  167.17  46.325 167.134      50 166.923
#Mann= 3 , 0 , 0
       0     .05       0   18.65     .03       0    31.6    .035       0
Bank Sta=18.65,31.6
XS Rating Curve= 0 ,0
Exp/Cntr=0.3,0.1

Type RM Length L Ch R = 1 ,300     ,21.305,20,18.744
XS GIS Cut Line= 3
1135768.828424181696799.083124211135791.383321511696809.86628732
1135813.938218831696820.64945043
#Sta/Elev= 19
       0 167.418   2.246 167.237   3.103  167.22    17.9 166.407  18.017   166.4
  18.761 166.035  19.307 165.918  19.904 165.787  22.547 165.854      25 165.941
  25.015 165.941  28.755  165.87   30.13 165.818  31.624 165.848      32 165.962
  32.417 166.089  32.691 166.136  39.914 166.256      50 166.788
#Mann= 3 , 0 , 0
       0     .05       0    17.9     .03       0      32    .035       0
Bank Sta=17.9,32
XS Rating Curve= 0 ,0
Exp/Cntr=0.3,0.1

Type RM Length L Ch R = 1 ,280     ,21.602,20,18.404
XS GIS Cut Line= 3
1135781.15931448 1696778.14712021135801.51843357 1696792.6559544
1135821.87755266 1696807.1647886
#Sta/Elev= 21
       0 168.304   1.619 168.225  15.233 166.987  16.158  166.48   17.35 166.049
  17.639 165.944   18.45 165.771  19.133 165.582  19.782  165.56   23.77 165.677
      25 165.751  25.313  165.77  27.504 165.695   30.21 165.761  32.128 165.818
   32.55 165.893  32.622 165.906  32.789 166.018  35.415 166.039  37.098 166.018
      50 166.256
#Mann= 3 , 0 , 0
       0     .05       0   17.35     .03       0   32.55    .035       0
Bank Sta=17.35,32.55
XS Rating Curve= 0 ,0
Exp/Cntr=0.3,0.1

Type RM Length L Ch R = 1 ,260     ,27.7,20,12.962
XS GIS Cut Line= 3
1135797.073316261696758.527779611135813.919384851696776.99964939
1135827.655464051696792.06138709
#Sta/Elev= 19
       0 169.252  10.064 168.522  15.083 166.728  16.442 166.265  17.337 165.936
  17.558 165.854   19.18  165.18  19.666 165.046  20.164 165.032  24.273 165.113
      25 165.165  25.198 165.179  30.671 165.555  31.174 165.572  32.823 165.788
  32.858 165.813  38.556 166.247  44.856 166.281  45.385 166.272
#Mann= 3 , 0 , 0
       0     .05       0  17.337     .03       0  32.823    .035       0
Bank Sta=17.337,32.823
XS Rating Curve= 0 ,0
Exp/Cntr=0.3,0.1

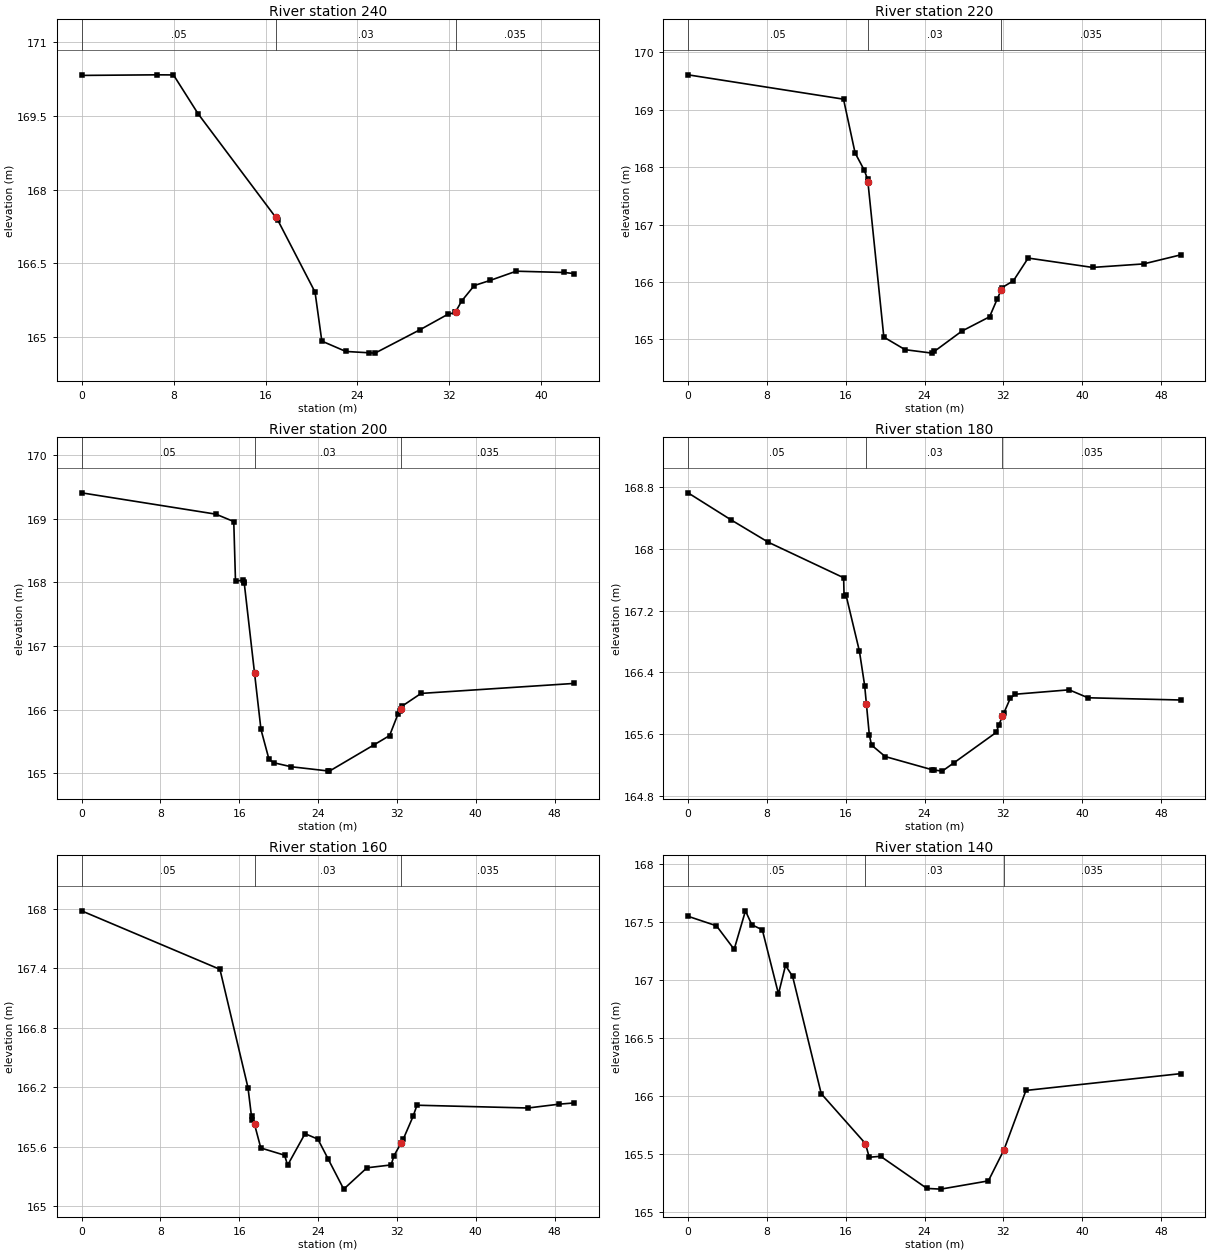
Type RM Length L Ch R = 1 ,240     ,22.058,20,18.055
XS GIS Cut Line= 3
1135837.355718721696749.506987411135832.708431041696774.07124431
 1135829.38848091696791.61956793
#Sta/Elev= 21
       0 170.325    6.56 170.337   7.996 170.335   10.14 169.543  16.887 167.436
  17.063 167.381  20.308 165.914  20.899 164.916  22.988 164.705      25 164.678
  25.527 164.671   29.46  165.15  31.833 165.458    32.5   165.5   32.53 165.512
  33.066 165.733  34.158 166.047  35.523  166.15  37.805 166.339   41.98 166.313
   42.86  166.29
#Mann= 3 , 0 , 0
       0     .05       0  16.887     .03       0   32.53    .035       0
Bank Sta=16.887,32.53
XS Rating Curve= 0 ,0
Exp/Cntr=0.3,0.1

Type RM Length L Ch R = 1 ,220     ,18.945,20,21.086
XS GIS Cut Line= 3
1135862.713673581696758.234465371135851.541947861696780.59945015
1135840.370222131696802.96443493
#Sta/Elev= 20
       0 169.609  15.778 169.185  16.953 168.248  17.886 167.947  18.226 167.788
   18.25 167.749  19.869  165.04  22.028 164.821  24.758 164.761      25 164.792
  27.782 165.144  30.599 165.394  31.389 165.709   31.75 165.852   31.88 165.904
  33.014 166.021  34.515 166.417  41.048 166.254  46.229 166.315      50 166.473
#Mann= 3 , 0 , 0
       0     .05       0   18.25     .03       0   31.75    .035       0
Bank Sta=18.25,31.75
XS Rating Curve= 0 ,0
Exp/Cntr=0.3,0.1

Type RM Length L Ch R = 1 ,200     ,20.414,20,19.6
XS GIS Cut Line= 3
1135877.967839221696763.664533751135870.295955051696787.45827648
1135862.624070881696811.25201922
#Sta/Elev= 22
       0 169.405  13.634  169.07  15.445 168.954  15.621 168.014  16.427 168.038
  16.487 168.005  16.511 167.985   17.55 166.578  18.205  165.69  19.023 165.219
  19.519 165.167  21.258 165.105      25 165.039   25.15 165.036  29.701 165.451
  31.256 165.594  32.103  165.93   32.29 165.987    32.4 166.019  32.532 166.057
   34.45 166.256      50 166.413
#Mann= 3 , 0 , 0
       0     .05       0   17.55     .03       0    32.4    .035       0
Bank Sta=17.55,32.4
XS Rating Curve= 0 ,0
Exp/Cntr=0.3,0.1

Type RM Length L Ch R = 1 ,180     ,21.021,20,19.012
XS GIS Cut Line= 3
1135898.177332131696770.774333911135889.160039721696794.09146146
 1135880.14274731696817.40858902
#Sta/Elev= 25
       0 168.729   4.346  168.38   8.154 168.088   15.79 167.628  15.834 167.396
  16.034 167.402   17.39 166.677  17.923 166.231    18.1 165.992  18.397  165.59
  18.626 165.458  20.006  165.31  24.797 165.138      25 165.135  25.796 165.121
  26.985 165.229  31.295 165.625  31.521 165.714    31.9  165.83  32.035 165.871
    32.7 166.065  33.214 166.118  38.672 166.175  40.584 166.072      50 166.043
#Mann= 3 , 0 , 0
       0     .05       0    18.1     .03       0    31.9    .035       0
Bank Sta=18.1,31.9
XS Rating Curve= 0 ,0
Exp/Cntr=0.3,0.1

Type RM Length L Ch R = 1 ,160     ,21.299,20,20.857
XS GIS Cut Line= 3
1135919.975713441696779.095728381135907.92220125 1696800.9980763
1135895.868689071696822.90042421
#Sta/Elev= 23
       0 167.977  14.042 167.387   16.89 166.193  17.294 165.863  17.333 165.907
   17.55 165.825  18.187 165.586  20.604 165.513  20.906 165.412  22.676  165.73
  23.981 165.675      25 165.479  26.601 165.171  28.958 165.386  31.409 165.415
  31.704 165.508    32.4 165.632  32.648 165.676  33.637 165.904  34.034 166.017
  45.307 165.989  48.488 166.028      50  166.04
#Mann= 3 , 0 , 0
       0     .05       0   17.55     .03       0    32.4    .035       0
Bank Sta=17.55,32.4
XS Rating Curve= 0 ,0
Exp/Cntr=0.3,0.1

Type RM Length L Ch R = 1 ,140     ,20.241,20,20.005
XS GIS Cut Line= 3
 1135934.7170662 1696787.05709411135925.543298111696810.31310363
1135916.369530021696833.56911315
#Sta/Elev= 19
       0 167.549   2.884 167.467   4.681 167.264   5.829 167.596   6.471 167.476
    7.54 167.432   9.177  166.88   9.892 167.125  10.611 167.031  13.516 166.019
      18 165.589  18.386 165.471  19.543 165.479   24.24 165.202  25.648 165.196
  30.475 165.267   32.05 165.533  34.289 166.047      50 166.192
#Mann= 3 , 0 , 0
       0     .05       0      18     .03       0   32.05    .035       0
Bank Sta=18,32.05
XS Rating Curve= 0 ,0
Exp/Cntr=0.3,0.1

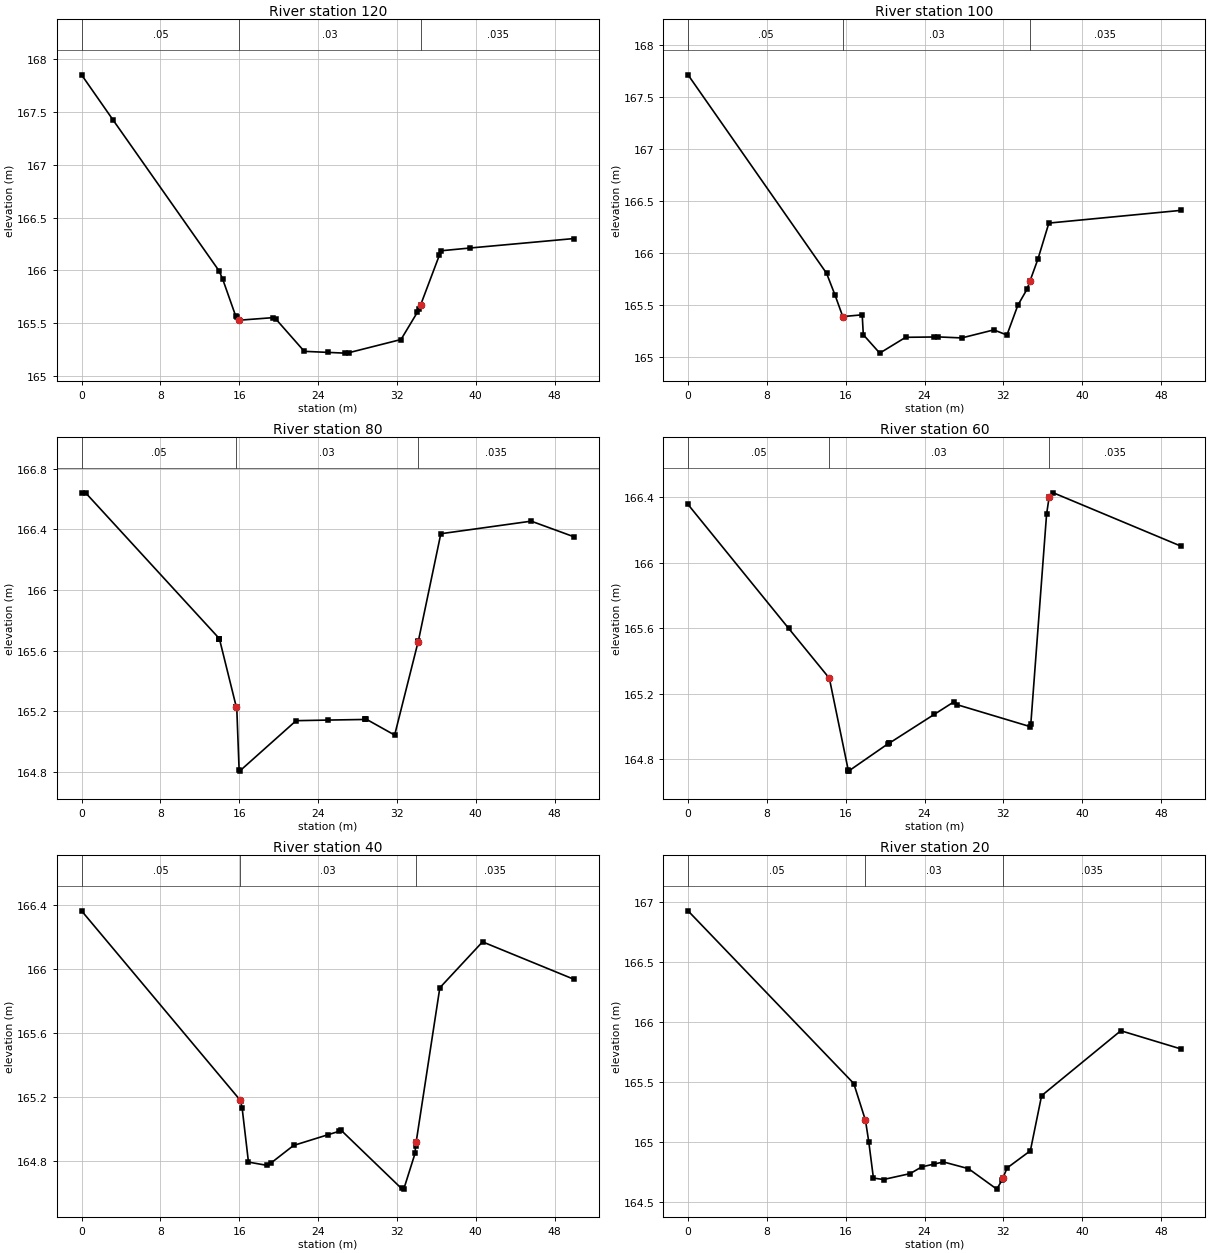
Type RM Length L Ch R = 1 ,120     ,18.77,20,21.322
XS GIS Cut Line= 3
1135953.586157981696795.398225431135943.820913931696818.41213445
1135934.055669881696841.42604348
#Sta/Elev= 22
       0 167.853   3.228 167.421  13.941 165.997  14.309  165.92   15.65 165.565
  15.788 165.554  15.984 165.534  16.005 165.528  19.404 165.552  19.743 165.536
  22.599 165.233      25 165.223  26.698 165.216  27.121  165.22  32.415 165.345
   34.08 165.604  34.263 165.637    34.4 165.671   36.32 166.147   36.49 166.186
  39.408 166.212      50 166.302
#Mann= 3 , 0 , 0
       0     .05       0  16.005     .03       0    34.4    .035       0
Bank Sta=16.005,34.4
XS Rating Curve= 0 ,0
Exp/Cntr=0.3,0.1

Type RM Length L Ch R = 1 ,100     ,20.411,20,19.61
XS GIS Cut Line= 3
1135969.471825171696800.356376971135962.865505751696824.46771339
1135956.25918634 1696848.5790498
#Sta/Elev= 19
       0 167.712  14.058 165.806  14.907 165.599  15.704  165.39  17.675 165.407
  17.786 165.216  19.454 165.039  22.082 165.191      25 165.194  25.318 165.195
  27.774 165.185  31.025 165.262  32.361 165.213  33.468 165.499    34.4 165.653
    34.7 165.732  35.505 165.942  36.614 166.288      50  166.41
#Mann= 3 , 0 , 0
       0     .05       0  15.704     .03       0    34.7    .035       0
Bank Sta=15.704,34.7
XS Rating Curve= 0 ,0
Exp/Cntr=0.3,0.1

Type RM Length L Ch R = 1 ,80      ,18.517,20,21.837
XS GIS Cut Line= 3
1135989.703338581696806.373250611135982.03496815  1696830.168126
1135974.36659773 1696853.9630014
#Sta/Elev= 22
       0 166.641    .412 166.642  13.977  165.68   13.98  165.68  13.986 165.679
    15.7 165.229  15.712 165.226  15.747 165.226  15.989  164.81  16.037 164.805
  21.772 165.138      25 165.142   28.73 165.146  28.796 165.146  28.884 165.148
  31.769 165.043  34.145 165.657  34.158 165.659  34.173 165.663  36.454 166.372
  45.628 166.455      50 166.351
#Mann= 3 , 0 , 0
       0     .05       0    15.7     .03       0  34.145    .035       0
Bank Sta=15.7,34.145
XS Rating Curve= 0 ,0
Exp/Cntr=0.3,0.1

Type RM Length L Ch R = 1 ,60      ,19.943,20,20.348
XS GIS Cut Line= 3
1136005.357614621696810.647258451136001.333092351696835.32119653
1135997.308570091696859.99513461
#Sta/Elev= 20
       0 166.357  10.203 165.601    14.3 165.299   14.34 165.296  16.264 164.733
  16.269  164.73  16.287 164.729  20.318 164.897  20.346 164.898  20.403 164.899
      25 165.076  27.008 165.153  27.333 165.134  34.701 165.001  34.785 165.018
  36.384 166.298  36.635 166.399   36.65   166.4  37.074 166.428      50 166.103
#Mann= 3 , 0 , 0
       0     .05       0    14.3     .03       0   36.65    .035       0
Bank Sta=14.3,36.65
XS Rating Curve= 0 ,0
Exp/Cntr=0.3,0.1

Type RM Length L Ch R = 1 ,40      ,20.434,20,19.76
XS GIS Cut Line= 3
1136024.666349181696813.891068551136021.056421551696838.62906407
1136017.446493921696863.36705959
#Sta/Elev= 19
       0 166.365    16.1 165.181  16.136 165.179  16.295 165.132  16.936 164.794
  18.867 164.773  19.197 164.787  21.511 164.898      25 164.965  26.103 164.986
  26.321 164.994  32.466 164.629  32.696 164.625  33.837 164.848  33.896 164.896
   33.95 164.918  36.354 165.884  40.687 166.171      50 165.936
#Mann= 3 , 0 , 0
       0     .05       0    16.1     .03       0   33.95    .035       0
Bank Sta=16.1,33.95
XS Rating Curve= 0 ,0
Exp/Cntr=0.3,0.1

Type RM Length L Ch R = 1 ,20      ,,,
XS GIS Cut Line= 3
1136045.384867521696817.57206587 1136040.73879511696842.13655266
1136036.092722681696866.70103945
#Sta/Elev= 19
       0 166.923   16.82 165.487  18.008  165.18  18.347 164.999  18.812 164.701
  19.836 164.689  22.534 164.738   23.72 164.794      25 164.818  25.919 164.835
   28.46 164.779  31.329 164.609  31.844 164.681   31.95 164.702  32.379 164.785
  34.738 164.928  35.877 165.386  43.914 165.926      50 165.775
#Mann= 3 , 0 , 0
       0     .05       0  18.008     .03       0   31.95    .035       0
Bank Sta=18.008,31.95
XS Rating Curve= 0 ,0
Exp/Cntr=0.3,0.1
LCMann Table=0

Chan Stop Cuts=-1
Use User Specified Reach Order=0
Composite Channel Slope=5